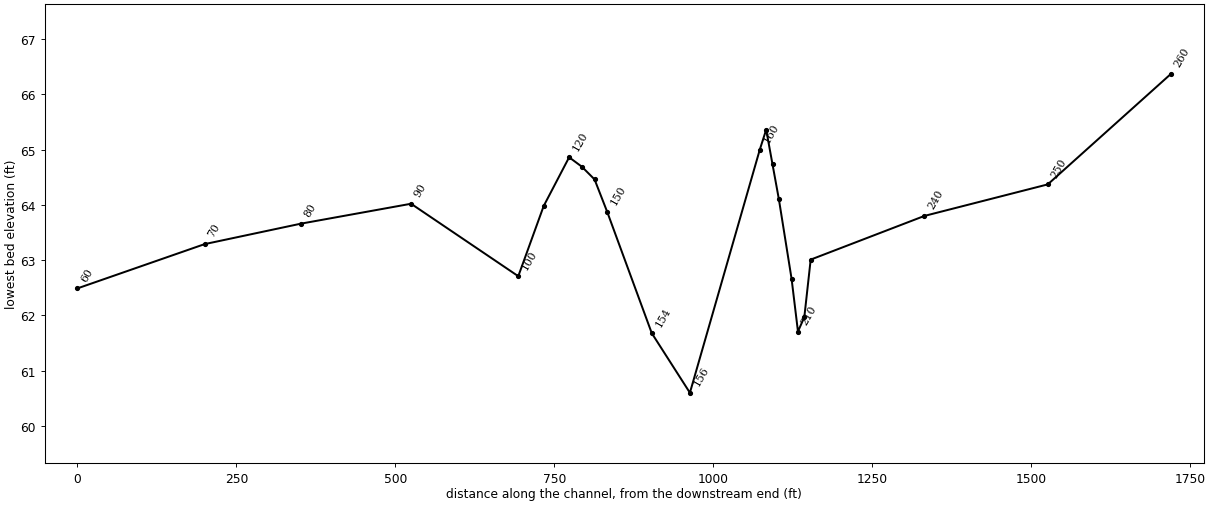
--- S45MultipleBr.prj (project) ---

Proj Title=S45 Multiple Br
Current Plan=p04
Default Exp/Contr=0.3,0.1
English Units
Geom File=g03
Geom File=g01
Geom File=g04
Geom File=g07
Flow File=f01
Flow File=f02
Plan File=p02
Plan File=p03
Plan File=p01
Plan File=p04
Plan File=p06
Y Axis Title=Elevation
X Axis Title(PF)=Main Channel Distance
X Axis Title(XS)=Station
BEGIN DESCRIPTION:
S45 - Multiple Opening Bridges
END DESCRIPTION:
DSS Export Rating Curves= 0
DSS Export Rating Curve Sorted= 0
DSS Export Volume Flow Curves= 0
DXF OffsetX= 0
DXF OffsetY= 0
DXF ScaleX= 1
DXF ScaleY= 10

--- S45MultipleBr.p04 (plan) ---

Plan Title=Proposed
Program Version=5.01
Short Identifier=Prop
Geom File=g04
Flow File=f01
Subcritical Flow
K Sum by GR= 0
Std Step Tol= 0.01
Critical Tol= 0.01
Num of Std Step Trials= 20
Max Error Tol= 0.3
Flow Tol Ratio= 0.001
Split Flow NTrial= 30
Split Flow Tol= 0.02
Split Flow Ratio= 0.02
Log Output Level= 0
Friction Slope Method= 1
Unsteady Friction Slope Method= 2
Unsteady Bridges Friction Slope Method= 1
Parabolic Critical Depth
Global Vel Dist= 0 , 0 , 0
Global Log Level= 0
CheckData=True
Encroach Param=-1 ,0,0, 0
Computation Interval=1MIN
Output Interval=1HOUR
Instantaneous Interval=1HOUR
Mapping Interval=1HOUR
Run HTab= 0
Run UNet= 0
Run Sediment= 0
Run PostProcess= 0
Run WQNet= 0
Run RASMapper= 0
UNET Theta= 1
UNET Theta Warmup= 1
UNET ZTol= 0.02
UNET ZSATol= 0.02
UNET MxIter= 20
UNET Max Iter WO Improvement= 0
UNET MaxInSteps= 0
UNET DtIC= 0
UNET DtMin= 0
UNET MaxCRTS= 20
UNET WFStab= 2
UNET SFStab= 1
UNET WFX= 1
UNET SFX= 1
UNET DSS MLevel= 4
UNET Pardiso=0
UNET DZMax Abort= 100
UNET Use Existing IB Tables=-1
UNET Froude Reduction=False
UNET Froude Limit= 0.8
UNET Froude Power= 4
UNET Time Slicing=0,0, 5
UNET Junction Losses=0
UNET D1 Cores= 0
UNET D2 Coriolis=0
UNET D2 Cores= 0
UNET D2 Theta= 1
UNET D2 Theta Warmup= 1
UNET D2 Z Tol= 0.01
UNET D2 Volume Tol= 0.01
UNET D2 Max Iterations= 20
UNET D2 Equation= 0
UNET D2 RampUpFraction=0.1
UNET D2 TimeSlices= 1
UNET D2 BCVolumeCheck=0
UNET D1D2 MaxIter= 0
UNET D1D2 ZTol=0.01
UNET D1D2 QTol=0.1
UNET D1D2 MinQTol=1
Write IC File= 0
Write IC File at Fixed DateTime=0
Write IC File at Sim End=0
Echo Input=False
Echo Parameters=False
Echo Output=False
Write Detailed= 0
HDF Write Warmup=0
HDF Write Time Slices=0
HDF Flush=0
HDF Face Node Velocities=0
HDF Compression= 1
HDF Chunk Size= 1
HDF Spatial Parts= 1
HDF Use Max Rows=0
HDF Fixed Rows= 1
Calibration Method= 0
Calibration Iterations= 20
Calibration Max Change=0.05
Calibration Tolerance=0.2
Calibration Maximum=1.5
Calibration Minimum=0.5
Calibration Optimization Method= 1
WQ AD Non Conservative
WQ ULTIMATE=-1
WQ Max Comp Step=1HOUR
WQ Output Interval=15MIN
WQ Output Selected Increments= 0
WQ Output face flow=0
WQ Output face velocity=0
WQ Output face area=0
WQ Output face dispersion=0
WQ Output cell volume=0
WQ Output cell surface area=0
WQ Output cell continuity=0
WQ Output cumulative cell continuity=0
WQ Output face conc=0
WQ Output face dconc_dx=0
WQ Output face courant=0
WQ Output face peclet=0
WQ Output face adv mass=0
WQ Output face disp mass=0
WQ Output cell mass=0
WQ Output cell source sink temp=0
WQ Output nsm pathways=0
WQ Output nsm derived pathways=0
WQ Output MaxMinRange=-1
WQ Daily Max Min Mean=-1
WQ Daily Range=0
WQ Daily Time=0
WQ Create Restart=0
WQ Fixed Restart=0
WQ System Summary=0
WQ Write To DSS=0
WQ Use Fixed Temperature=0
Sorting and Armoring Iterations= 10
XS Update Threshold= 0.02
Bed Roughness Predictor= 0
Hydraulics Update Threshold= 0.02
Energy Slope Method= 1
Volume Change Method= 1
Sediment Retention Method= 0
XS Weighting Method= 0
Number of US Weighted Cross Sections= 1
Number of DS Weighted Cross Sections= 1
Upstream XS Weight=0
Main XS Weight=1
Downstream XS Weight=0
Number of DS XS's Weighted with US Boundary= 1
Upstream Boundary Weight= 1
Weight of XSs Associated with US Boundary= 0
Number of US XS's Weighted with DS Boundary= 1
Downstream Boundary Weight= 0.5
Weight of XSs Associated with DS Boundary= 0.5
Percentile Method= 0
Sediment Output Level= 4
Mass or Volume Output= 0
Output Increment Type= 1
Profile and TS Output Increment= 1
XS Output Flag= 0
XS Output Increment= 10
Write Gradation File= 0
Read Gradation Hotstart= 0
Write HDF5 File= 1
Write DSS Sediment File= 0
SV Curve= 0
Specific Gage Flag= 0

--- S45MultipleBr.p01 (plan) ---

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Plan Title=Existing-PW
Short Identifier=Exst-PW
Geom File=g01
Flow File=f01

--- S45MultipleBr.p02 (plan) ---

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Plan Title=Natural
Short Identifier=Nat
Geom File=g07
Flow File=f01

--- S45MultipleBr.p03 (plan) ---

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Plan Title=Existing
Short Identifier=Exst
Geom File=g03
Flow File=f01

--- S45MultipleBr.p06 (plan) ---

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Plan Title=Proposed-Converge
Short Identifier=Prop-Con
Geom File=g04
Flow File=f02

--- S45MultipleBr.f01 (steady flow) ---

Flow Title=Flow
Program Version=5.01
Number of Profiles= 4
Profile Names=25 Yr,50 Yr,100 Yr,500 Yr
River Rch & RM=Little Pee Dee,S45             ,260
    7197    8609   10168   14105
Boundary for River Rch & Prof#=Little Pee Dee,S45             , 1
Up Type= 0
Dn Type= 3
Dn Slope=0.0003
Boundary for River Rch & Prof#=Little Pee Dee,S45             , 2
Up Type= 0
Dn Type= 3
Dn Slope=0.0003
Boundary for River Rch & Prof#=Little Pee Dee,S45             , 3
Up Type= 0
Dn Type= 3
Dn Slope=0.0003
Boundary for River Rch & Prof#=Little Pee Dee,S45             , 4
Up Type= 0
Dn Type= 3
Dn Slope=0.0003
DSS Import GetInterval= 0
DSS Import GetPeak= 0
DSS Import FillOption= 0

--- S45MultipleBr.f02 (steady flow) ---

Flow Title=Flow-Converge
Program Version=5.01
Number of Profiles= 14
Profile Names=25 Yr(-1),25 Yr(-2),25 Yr(-3),25 Yr(+1),25 Yr(+2),25 Yr(+3),100 Yr(-1),100 Yr(-2),100 Yr(-3),100 Yr(+1),100 Yr(+2),100 Yr(+3),25 Yr(0),100 Yr(0)
River Rch & RM=Little Pee Dee,S45             ,260
    7197    7197    7197    7197    7197    7197   10168   10168   10168   10168
   10168   10168    7197   10168
Boundary for River Rch & Prof#=Little Pee Dee,S45             , 1
Up Type= 0
Dn Type= 1
Dn Known WS=73.89
Boundary for River Rch & Prof#=Little Pee Dee,S45             , 2
Up Type= 0
Dn Type= 1
Dn Known WS=72.89
Boundary for River Rch & Prof#=Little Pee Dee,S45             , 3
Up Type= 0
Dn Type= 1
Dn Known WS=71.89
Boundary for River Rch & Prof#=Little Pee Dee,S45             , 4
Up Type= 0
Dn Type= 1
Dn Known WS=75.89
Boundary for River Rch & Prof#=Little Pee Dee,S45             , 5
Up Type= 0
Dn Type= 1
Dn Known WS=76.89
Boundary for River Rch & Prof#=Little Pee Dee,S45             , 6
Up Type= 0
Dn Type= 1
Dn Known WS=77.89
Boundary for River Rch & Prof#=Little Pee Dee,S45             , 7
Up Type= 0
Dn Type= 1
Dn Known WS=75
Boundary for River Rch & Prof#=Little Pee Dee,S45             , 8
Up Type= 0
Dn Type= 1
Dn Known WS=74
Boundary for River Rch & Prof#=Little Pee Dee,S45             , 9
Up Type= 0
Dn Type= 1
Dn Known WS=73
Boundary for River Rch & Prof#=Little Pee Dee,S45             , 10
Up Type= 0
Dn Type= 1
Dn Known WS=77
Boundary for River Rch & Prof#=Little Pee Dee,S45             , 11
Up Type= 0
Dn Type= 1
Dn Known WS=78
Boundary for River Rch & Prof#=Little Pee Dee,S45             , 12
Up Type= 0
Dn Type= 1
Dn Known WS=79
Boundary for River Rch & Prof#=Little Pee Dee,S45             , 13
Up Type= 0
Dn Type= 1
Dn Known WS=74.89
Boundary for River Rch & Prof#=Little Pee Dee,S45             , 14
Up Type= 0
Dn Type= 1
Dn Known WS=76
DSS Import GetInterval= 0
DSS Import GetPeak= 0
DSS Import FillOption= 0

--- S45MultipleBr.g04 (geometry) ---

Geom Title=Proposed
Program Version=5.01

River Reach=Little Pee Dee  ,S45
Reach XY= 3
0.055131004366810.863537117903930.840065502183410.46615720524018
0.840065502183410.46615720524018

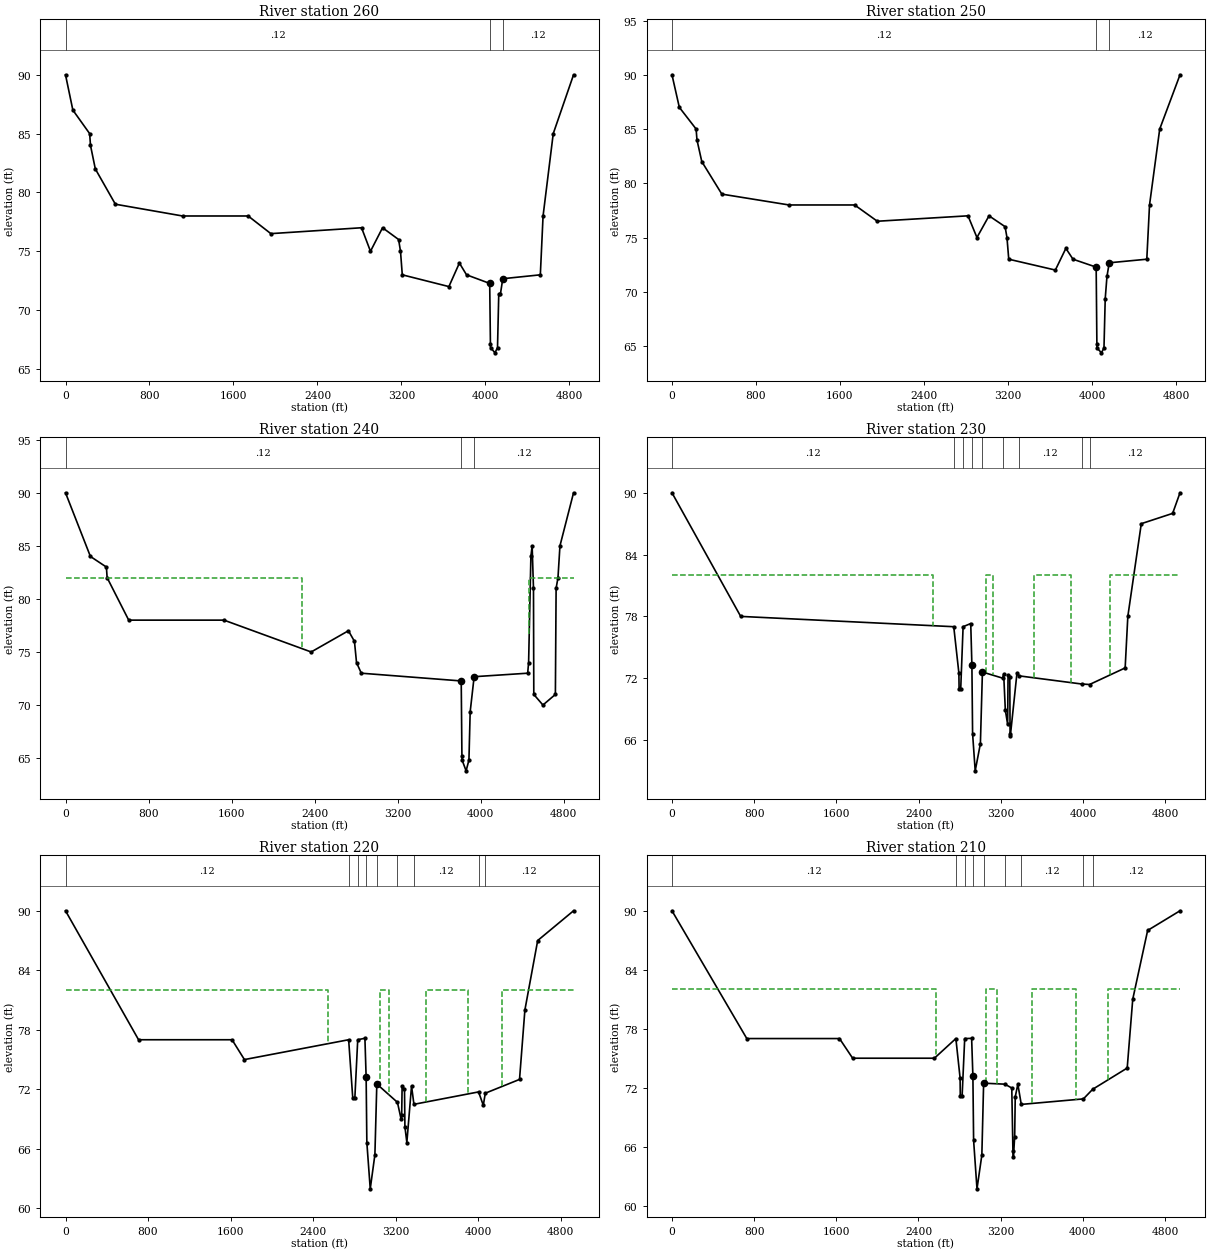
Type RM Length L Ch R = 1 ,260     ,87.36,194,87.36
BEGIN DESCRIPTION:
Upstream
END DESCRIPTION:
#Sta/Elev= 30
       0      90      70      87     230      85     238      84     284      82
     475      79    1115      78    1740      78    1956    76.5    2820      77
    2905      75    3020      77    3173      76    3191      75    3208      73
    3652      72    3752      74    3820      73 4040.72   72.27 4047.51   67.16
 4048.95   66.82 4090.86   66.37 4115.08   66.82 4126.94   71.36 4143.52   71.41
 4165.15   72.67    4523      73    4549      78    4646      85 4839.38      90
#Mann= 3 , 0 , 0
       0     .12       0 4040.72     .05       0 4165.15     .12       0
Bank Sta=4040.72,4165.15
XS Rating Curve= 0 ,0
Exp/Cntr=0.3,0.1

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
Type RM Length L Ch R = 1 ,250     ,112.2,194,148.4
#Sta/Elev= 30
       0      90      70      87     230      85     238      84     284      82
     475      79    1115      78    1740      78    1956    76.5    2820      77
    2905      75    3020      77    3173      76    3191      75    3208      73
    3652      72    3752      74    3820      73 4040.72   72.27 4047.51   65.16
 4048.95   64.82 4090.86   64.37 4115.08   64.82 4126.94   69.36 4143.52   71.41
 4165.15   72.67    4523      73    4549      78    4646      85 4839.38      90
#Mann= 3 , 0 , 0
       0     .12       0 4040.72     .05       0 4165.15     .12       0
Bank Sta=4040.72,4165.15
XS Rating Curve= 0 ,0
Exp/Cntr=0.5,0.3

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
Type RM Length L Ch R = 1 ,240     ,18.67,179,27.89
#Sta/Elev= 30
       0      90     240      84     394      83     401      82     609      78
    1527      78    2367      75    2726      77    2784      76    2804      74
    2850      73 3812.72   72.27 3819.51   65.16 3820.95   64.82 3859.85    63.8
 3887.08   64.82 3898.94   69.36 3937.15   72.67    4453      73    4462      74
    4484      84    4496      85    4509      81    4512      71    4600      70
    4720      71    4727      81    4745      82    4764      85    4895      90
#Mann= 3 , 0 , 0
       0     .12       0 3812.72     .05       0 3937.15     .12       0
#XS Ineff= 2 ,-1
       0    2283      82    4468    4895      82
Permanent Ineff=
       F       F
Bank Sta=3812.72,3937.15
XS Rating Curve= 0 ,0
Exp/Cntr=0.5,0.3

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
Type RM Length L Ch R = 1 ,230     ,8,10,20
BEGIN DESCRIPTION:
Stn 12+90
END DESCRIPTION:
#Sta/Elev= 30
       0      90   668.8      78    2742      77    2792    72.5    2794      71
    2810      71    2833      77 2907.37   77.31 2918.64   73.26 2925.36   66.62
 2950.79   63.01 3001.36   65.65 3021.02    72.6 3217.03   72.01 3228.08   72.37
 3243.87   68.92 3266.36   67.52 3270.55    72.3 3287.33   72.11 3290.27   66.54
  3293.1   66.43 3357.36   72.51 3377.02   72.23 3985.41   71.44 4063.55   71.39
    4410      73    4436      78    4567      87    4872      88 4943.86      90
#Mann= 9 ,-1 , 0
       0     .12       0    2742     .05       0    2833     .12       0
 2918.64     .05       0 3021.02     .12       0 3217.03     .05       0
 3377.02     .12       0 3985.41     .05       0 4063.55     .12       0
#XS Ineff= 4 ,-1
       0    2536      82    3056    3120      82    3519    3880      82
    4260 4943.86      82
Permanent Ineff=
       F       F       F       F
Bank Sta=2918.64,3021.02
XS Rating Curve= 0 ,0
Exp/Cntr=0.5,0.3

Type RM Length L Ch R = 1 ,220     ,6,10,10
BEGIN DESCRIPTION:
Stn 13+00
END DESCRIPTION:
#Sta/Elev= 30
       0      90     708      77    1614      77    1734      75    2744      77
    2784    71.1    2804    71.1    2832      77 2901.64   77.15 2913.56    73.2
 2920.34   66.64 2953.23   61.97  2998.4   65.41 3016.98   72.54 3216.92   70.69
  3252.6   68.98 3257.85   69.37 3262.23    72.3 3285.22   72.02 3289.36   68.22
 3308.06   66.64 3353.49   72.34 3376.68   70.49 4003.07   71.74 4048.96   70.39
 4068.31   71.61    4400      73    4452      80    4576      87 4923.55      90
#Mann= 9 ,-1 , 0
       0     .12       0    2744     .05       0    2832     .12       0
 2913.56     .05       0 3016.98     .12       0 3216.92     .05       0
 3376.68     .12       0 4003.07     .05       0 4068.31     .12       0
#XS Ineff= 4 ,-1
       0    2544      82    3047    3133      82    3494    3898      82
    4234 4923.55      82
Permanent Ineff=
       F       F       F       F
Bank Sta=2913.56,3016.98
XS Rating Curve= 0 ,0
Exp/Cntr=0.5,0.3

Type RM Length L Ch R = 1 ,210     ,8,10,10
BEGIN DESCRIPTION:
Stn 13+10
END DESCRIPTION:
#Sta/Elev= 30
       0      90   728.5      77    1631      77    1759      75    2555      75
    2764      77    2805      73    2807    71.2    2825    71.2    2850      77
 2917.46   77.02 2929.82   73.14 2936.64   66.65 2969.59   61.71 3016.91   65.14
 3034.24   72.46 3240.69   72.36 3308.33   71.97 3319.38   65.58 3324.41   64.95
 3336.43      67 3342.03   71.07 3367.41   72.36 3400.68    70.3 4005.49   70.86
 4095.98   71.84    4432      74    4486      81    4631      88 4946.23      90
#Mann= 9 ,-1 , 0
       0     .12       0    2764     .05       0    2850     .12       0
 2929.82     .05       0 3034.24     .12       0 3240.69     .05       0
 3400.68     .12       0 4005.49     .05       0 4095.98     .12       0
#XS Ineff= 4 ,-1
       0    2570      82    3060    3167      82    3507    3931      82
    4247 4946.23      82
Permanent Ineff=
       F       F       F       F
Bank Sta=2929.82,3034.24
XS Rating Curve= 0 ,0
Exp/Cntr=0.5,0.3

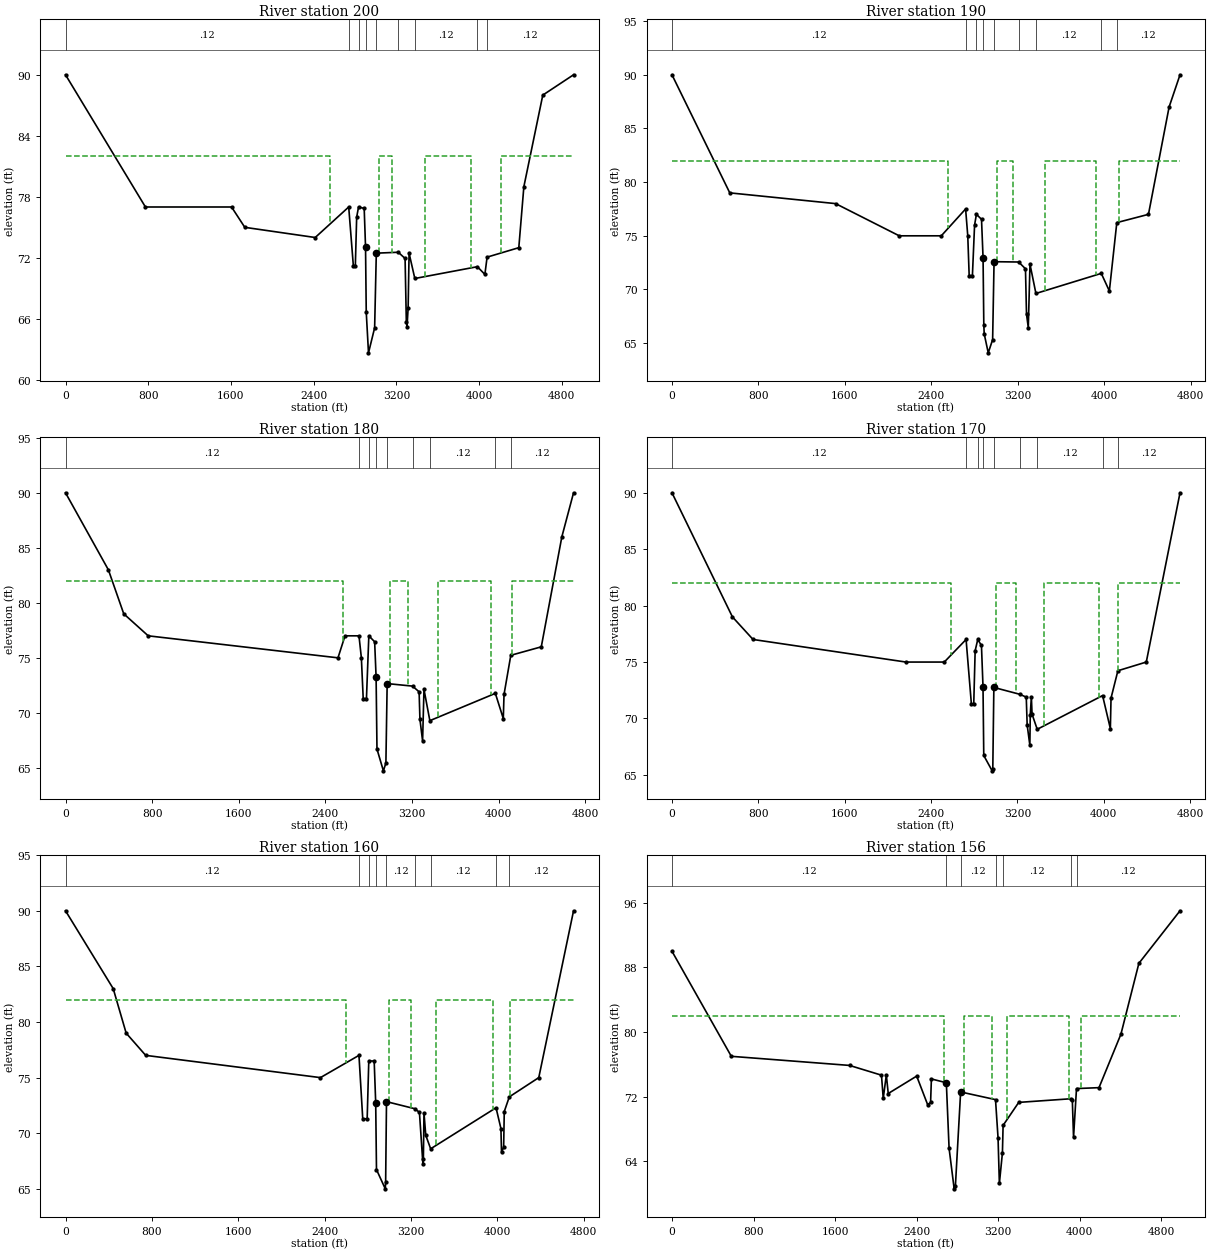
Type RM Length L Ch R = 1 ,200     ,15,20,50
BEGIN DESCRIPTION:
Stn 13+20
END DESCRIPTION:
#Sta/Elev= 30
       0      90     773      77    1606      77    1734      75    2415      74
    2739      77    2784    71.2    2803    71.2    2816      76    2834      77
 2888.71   76.86 2901.71   73.08 2908.59   66.66 2930.34   62.66 2989.71   65.12
  3005.9   72.46 3218.38   72.55 3284.13   71.94 3296.25   65.73 3302.91   65.22
 3313.75   67.09 3322.86   72.46 3378.38   69.97 3983.49   71.13 4055.94   70.37
 4077.34   72.07    4384      73    4433      79    4616      88 4913.48      90
#Mann= 9 ,-1 , 0
       0     .12       0    2739     .05       0    2834     .12       0
 2901.71     .05       0  3005.9     .12       0 3218.38     .05       0
 3378.38     .12       0 3983.49     .05       0 4077.34     .12       0
#XS Ineff= 4 ,-1
       0    2554      82    3030    3155      82    3474    3918      82
    4213 4913.48      82
Permanent Ineff=
       F       F       F       F
Bank Sta=2901.71,3005.9
XS Rating Curve= 0 ,0
Exp/Cntr=0.5,0.3

Type RM Length L Ch R = 1 ,190     ,8,10,10
BEGIN DESCRIPTION:
Stn 13+40
END DESCRIPTION:
#Sta/Elev= 30
       0      90     535      79    1514      78    2103      75    2492      75
    2717    77.5    2737      75    2750    71.3    2780    71.3    2800      76
    2817      77  2864.2   76.54 2878.48   72.95 2885.48   66.69 2889.15   65.87
 2926.42    64.1 2967.08   65.33 2980.28   72.59  3207.6   72.56  3270.9   71.93
 3280.47   67.71 3296.98   66.45 3312.77   72.35  3367.6   69.63 3972.36    71.5
 4047.17   69.86 4116.08   76.23    4409      77    4600      87 4700.93      90
#Mann= 9 ,-1 , 0
       0     .12       0    2717     .05       0    2817     .12       0
 2878.48     .05       0 2980.28     .12       0  3207.6     .05       0
  3367.6     .12       0 3972.36     .05       0 4116.08     .12       0
#XS Ineff= 4 ,-1
       0    2556      82    3003    3154      82    3450    3919      82
    4139 4700.93      82
Permanent Ineff=
       F       F       F       F
Bank Sta=2878.48,2980.28
XS Rating Curve= 0 ,0
Exp/Cntr=0.5,0.3

Type RM Length L Ch R = 1 ,180     ,9,10,10
BEGIN DESCRIPTION:
Stn 13+50
END DESCRIPTION:
#Sta/Elev= 30
       0      90     396      83     538      79     764      77    2517      75
    2582      77    2711      77    2733      75    2750    71.3    2780    71.3
    2802      77 2855.69   76.46 2869.15   73.23 2877.21   66.71 2936.37   64.73
 2959.62   65.44 2971.31   72.66 3205.61   72.43 3266.47   71.91 3273.94   69.42
 3298.54   67.45  3311.4   72.13 3365.61   69.29 3970.69   71.77 4044.06   69.48
  4050.8   71.67 4113.38   75.23    4395      76    4585      86 4693.01      90
#Mann= 9 ,-1 , 0
       0     .12       0    2711     .05       0    2802     .12       0
 2869.15     .05       0 2971.31     .12       0 3205.61     .05       0
 3365.61     .12       0 3970.69     .05       0 4113.38     .12       0
#XS Ineff= 4 ,-1
       0    2562      82    2994    3163      82    3437    3927      82
    4125 4693.01      82
Permanent Ineff=
       F       F       F       F
Bank Sta=2869.15,2971.31
XS Rating Curve= 0 ,0
Exp/Cntr=0.5,0.3

Type RM Length L Ch R = 1 ,170     ,10,10,10
BEGIN DESCRIPTION:
Stn 13+60
END DESCRIPTION:
#Sta/Elev= 30
       0      90     560      79     751      77    2167      75    2522      75
    2724      77    2773    71.3    2795    71.3    2808      76    2832      77
 2866.34   76.47 2880.74   72.81 2887.76   66.72 2965.58   65.36 2971.42   65.54
 2981.26   72.75  3222.9   72.14 3281.31   71.89 3289.71   69.43  3314.6   67.63
 3318.49   70.33 3328.69   71.93 3335.07   70.38  3382.9   69.04  3988.3   72.03
 4060.25    69.1 4066.53   71.81 4129.98   74.23    4393      75 4705.39      90
#Mann= 9 ,-1 , 0
       0     .12       0    2724     .05       0    2832     .12       0
 2880.74     .05       0 2981.26     .12       0  3222.9     .05       0
  3382.9     .12       0  3988.3     .05       0 4129.98     .12       0
#XS Ineff= 4 ,-1
       0    2588      82    3004    3189      82    3443    3953      82
    4131 4705.39      82
Permanent Ineff=
       F       F       F       F
Bank Sta=2880.74,2981.26
XS Rating Curve= 0 ,0
Exp/Cntr=0.5,0.3

Type RM Length L Ch R = 1 ,160     ,129.99,110.01,24.99
BEGIN DESCRIPTION:
Stn 13+70
END DESCRIPTION:
#Sta/Elev= 30
       0      90     442      83     562      79     743      77    2362      75
    2719      77    2754    71.3    2795    71.3    2810    76.5    2860   76.49
 2874.04   72.74 2881.32   66.73 2962.82      65 2966.23   65.64 2974.12   72.84
 3233.83   72.21  3279.2   71.88 3311.71    67.2 3315.76   67.66  3321.4   71.82
 3338.06   69.81 3383.23    68.6 3988.94   72.29 4034.42   70.42 4039.66    68.3
 4059.44   68.72 4065.28   71.95 4112.02   73.27    4385      75  4707.2      90
#Mann= 9 ,-1 , 0
       0     .12       0    2719     .05       0    2810     .12       0
 2874.04     .05       0 2974.12     .12       0 3233.83     .05       0
 3383.23     .12       0 3988.94     .05       0 4112.02     .12       0
#XS Ineff= 4 ,-1
       0    2597      82    2998    3199      82    3432    3963      82
    4123  4707.2      82
Permanent Ineff=
       F       F       F       F
Bank Sta=2874.04,2974.12
XS Rating Curve= 0 ,0
Exp/Cntr=0.5,0.3

Type RM Length L Ch R = 1 ,156     ,60,60,60
BEGIN DESCRIPTION:
Bridge - Upstream
END DESCRIPTION:
#Sta/Elev= 30
       0      90     582      77 1741.06 75.8743 2054.45 74.6666 2071.79 71.7957
 2102.06 74.6859 2120.88 72.3984 2399.79 74.5524 2507.24 71.0181 2536.19 71.3033
 2544.06    74.2 2690.58   73.73 2717.54 65.6107 2767.44 60.6025 2779.51 60.9536
 2830.78 72.5917 3172.78 71.6429 3197.71 66.8991 3210.64 61.2638 3240.62 65.0586
 3247.21 68.4574 3400.53    71.3 3913.63 71.7514 3926.05 71.6037 3938.04  66.967
 3967.04 73.0092 4187.68 73.1239 4402.62 79.7382 4578.71 88.5063 4982.15 95.0095
#Mann= 7 ,-1 , 0
       0     .12       0 2690.58     .05       0 2830.78     .12       0
 3172.78     .05       0 3247.21     .12       0 3913.63     .05       0
 3967.04     .12       0
#XS Ineff= 4 ,-1
       0    2665      82    2864    3141      82    3290    3890      82
    4007 4982.15      82
Permanent Ineff=
       F       F       F       F
Bank Sta=2690.58,2830.78
XS Rating Curve= 0 ,0
Exp/Cntr=0.5,0.3

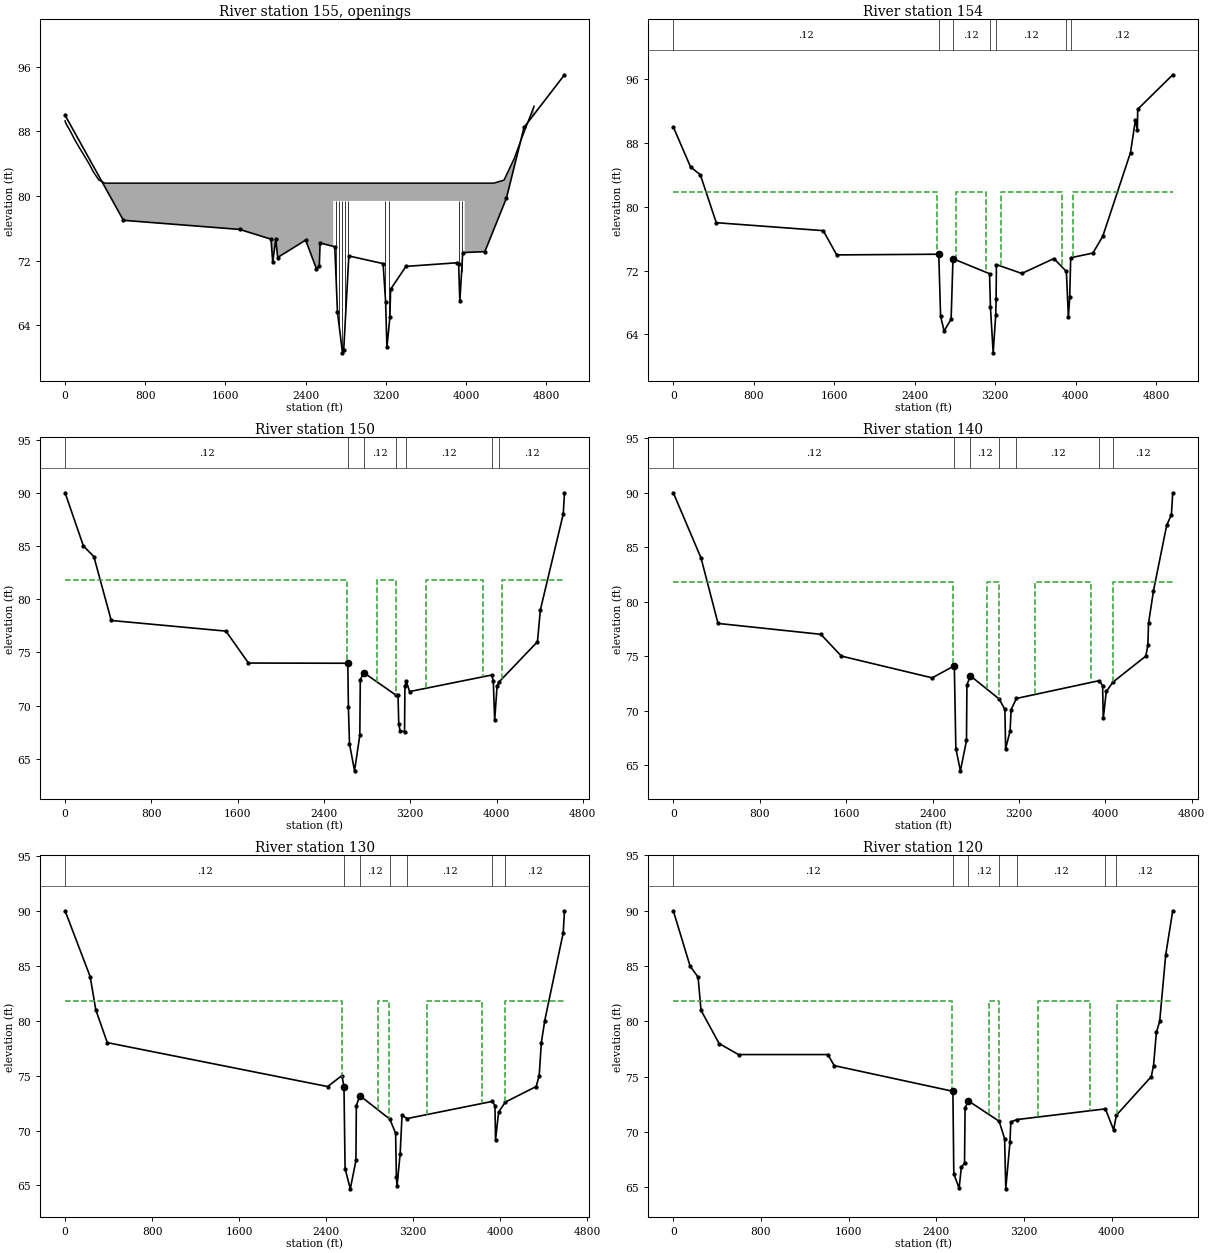
Type RM Length L Ch R = 4 ,155     ,,,
Bridge Culvert--1,0,-1,-1, 0
Deck Dist Width WeirC Skew NumUp NumDn MinLoCord MaxHiCord MaxSubmerge Is_Ogee
13,34,2.6,0, 55, 50, , , 0.98, 0, 0,0,,
       0       8      54      95     142     191     240     282     336     397
     475     839    1630    1779    1879    1979    2079    2179    2279    2379
    2479    2579  2674.8  2674.8  2854.8  2854.8    2879    2979    3079  3152.8
  3152.8  3152.8  3272.8  3272.8    3279    3329    3379    3429    3479    3579
    3679    3779    3879  3895.8  3895.8  3985.8  3985.8  3985.8    4079    4179
    4279    4379    4479    4579    4679
    89.3      89      88      87      86      85      84      83      82    81.6
    81.6    81.6    81.6    81.6    81.6    81.6    81.6    81.6    81.6    81.6
    81.6    81.6    81.6    81.6    81.6    81.6    81.6    81.6    81.6    81.6
    81.6    81.6    81.6    81.6    81.6    81.6    81.6    81.6    81.6    81.6
    81.6    81.6    81.6    81.6    81.6    81.6    81.6    81.6    81.6    81.6
    81.6   81.98    84.6   87.95   91.12
                                                                                
                                                                                
                            79.4    79.4
            79.4    79.4
                                    79.4    79.4
                                        
     240     282     336     397     475     839    1630    1779    1879    1979
    2079    2179    2279    2379    2479    2579  2625.3  2625.3  2805.3  2805.3
    2879    2979    3079  3127.8  3127.8  3247.8  3247.8    3279    3329    3379
    3429    3479    3579    3679    3779    3879  3879.9  3879.9  3969.9  3969.9
    3979    4079    4179    4279    4379    4479    4579    4679    4779    4879
      84      83      82    81.6    81.6    81.6    81.6    81.6    81.6    81.6
    81.6    81.6    81.6    81.6    81.6    81.6    81.6    81.6    81.6    81.6
    81.6    81.6    81.6    81.6    81.6    81.6    81.6    81.6    81.6    81.6
    81.6    81.6    81.6    81.6    81.6    81.6    81.6    81.6    81.6    81.6
    81.6    81.6    81.6    81.6   81.98    84.6   87.95   91.12   95.31   95.08
                                                                                
                                                            79.4    79.4
                                    79.4    79.4
                                                            79.4    79.4
                                                                                
Pier Skew, UpSta & Num, DnSta & Num=  ,2704.8, 2 ,2655.3, 2 , 0 , 0 , 0 ,,
    1.67    1.67
      60      80
    1.67    1.67
      60      80
Pier Skew, UpSta & Num, DnSta & Num=  ,2734.8, 2 ,2685.3, 2 , 0 , 0 , 0 ,,
    1.67    1.67
      60      80
    1.67    1.67
      60      80
Pier Skew, UpSta & Num, DnSta & Num=  ,2764.8, 2 ,2715.3, 2 , 0 , 0 , 0 ,,
    1.67    1.67
      60      80
    1.67    1.67
      60      80
Pier Skew, UpSta & Num, DnSta & Num=  ,2794.8, 2 ,2745.3, 2 , 0 , 0 , 0 ,,
    1.67    1.67
      60      80
    1.67    1.67
      60      80
Pier Skew, UpSta & Num, DnSta & Num=  ,2824.8, 2 ,2775.3, 2 , 0 , 0 , 0 ,,
    1.67    1.67
      60      80
    1.67    1.67
      60      80
Pier Skew, UpSta & Num, DnSta & Num=  ,3192.8, 2 ,3167.8, 2 , 0 , 0 , 0 ,,
    1.67    1.67
      60      80
    1.67    1.67
      60      80
Pier Skew, UpSta & Num, DnSta & Num=  ,3232.8, 2 ,3207.8, 2 , 0 , 0 , 0 ,,
    1.67    1.67
      60      80
    1.67    1.67
      60      80
Pier Skew, UpSta & Num, DnSta & Num=  ,3925.8, 2 ,3909.9, 2 , 0 , 0 , 0 ,,
    1.67    1.67
      60      80
    1.67    1.67
      60      80
Pier Skew, UpSta & Num, DnSta & Num=  ,3955.8, 2 ,3939.9, 2 , 0 , 0 , 0 ,,
    1.67    1.67
      60      80
    1.67    1.67
      60      80
Abutment Skew #Up #Dn= , 2 , 2
  2674.8  2679.8
    79.4      60
  2625.3  2630.3
    79.4      60
Abutment Skew #Up #Dn= , 2 , 2
  2849.8  2854.8
      60    79.4
  2800.3  2805.3
      60    79.4
Abutment Skew #Up #Dn= , 2 , 2
  3152.8  3157.8
    79.4      60
  3127.8  3132.8
    79.4      60
Abutment Skew #Up #Dn= , 2 , 2
  3267.8  3272.8
      60    79.4
  3242.8  3247.8
      60    79.4
Abutment Skew #Up #Dn= , 2 , 2
  3895.8  3900.8
    79.4      60
  3879.9  3884.9
    79.4      60
Abutment Skew #Up #Dn= , 2 , 2
  3980.8  3985.8
      60    79.4
  3964.9  3969.9
      60    79.4
BR Coef=-1 , 0 , 0 ,, 0 ,,,0.8,-1,,0,
WSPro=,,,, 1 ,,,, 0 ,,,, 0 ,,,,-1 ,-1 ,-1 , 0 , 0 , 0 , 0 , 0
BC Mult= 3 ,0,3095,0,3045.5
BC Mult= 3 ,2900,3700,2850.5,3650.5
BC Mult= 3 ,3400,4982.15,3350.5,4966.11
BC Design=,, 0 ,, 0 ,,,,,,
BC Use User HTab Curves=0
BC User HTab FreeFlow(D)= 0

Type RM Length L Ch R = 1 ,154     ,5,70,35
BEGIN DESCRIPTION:
Bridge - Downstream
END DESCRIPTION:
#Sta/Elev= 30
       0      90     171      85     269      84     427      78    1491      77
 1624.95 73.9596 2639.55 74.0448 2657.88 66.2491 2692.74 64.4206 2762.43 65.9018
 2780.89 73.4811 3144.53 71.6023 3153.45 67.3865 3180.54   61.68 3206.25 66.4675
 3209.74 68.3821 3212.84 72.7469 3465.52 71.6316 3784.49    73.5 3908.73  71.881
 3928.43 66.1158  3941.6 68.6294 3951.49    73.6  4172.4 74.1905 4270.42 76.2945
 4546.17 86.7895 4594.39 90.8314 4614.24 89.6382 4618.07 92.2247 4966.11 96.5451
#Mann= 7 ,-1 , 0
       0     .12       0 2639.55     .05       0 2780.89     .12       0
 3144.53     .05       0 3212.84     .12       0 3908.73     .05       0
 3951.49     .12       0
#XS Ineff= 4 ,-1
       0    2621    81.8    2810    3111    81.8    3260    3865    81.8
    3975 4966.11    81.8
Permanent Ineff=
       F       F       F       F
Bank Sta=2639.55,2780.89
XS Rating Curve= 0 ,0
Exp/Cntr=0.5,0.3

Type RM Length L Ch R = 1 ,150     ,16,20,18
BEGIN DESCRIPTION:
Stn 16+10
END DESCRIPTION:
#Sta/Elev= 30
       0      90     170      85     267      84     428      78    1491      77
    1700      74 2620.97   73.98 2626.37    69.9 2636.56   66.41 2683.42   63.87
 2732.31   67.22 2736.61   72.41    2767   73.11 3072.25   70.95  3086.5   70.96
 3093.21   68.29 3105.88   67.63 3146.86   67.54 3150.57   71.84  3162.9   72.31
  3193.6   71.32 3954.19   72.87 3969.57   72.32 3982.25   68.61 4005.13   71.88
 4026.35   72.26    4379      76    4406      79    4618      88 4629.68      90
#Mann= 7 ,-1 , 0
       0     .12       0 2620.97     .05       0    2767     .12       0
 3072.25     .05       0  3162.9     .12       0 3954.19     .05       0
 4026.35     .12       0
#XS Ineff= 4 ,-1
       0    2610    81.8    2895    3070    81.8    3343    3877    81.8
    4046 4629.68    81.8
Permanent Ineff=
       F       F       F       F
Bank Sta=2620.97,2767
XS Rating Curve= 0 ,0
Exp/Cntr=0.5,0.3

Type RM Length L Ch R = 1 ,140     ,18,20,10
BEGIN DESCRIPTION:
Stn 16+30
END DESCRIPTION:
#Sta/Elev= 30
       0      90     257      84     414      78    1366      77    1556      75
    2397      73 2601.95   74.11 2616.15   66.51  2658.4   64.46 2714.57   67.25
 2718.53   72.34    2750   73.19 3017.26   71.06 3070.21    70.1 3076.84   66.49
 3118.23   68.12 3127.89   70.09 3177.27   71.11 3942.06   72.74 3974.94   72.29
 3980.73   69.28 4009.21   71.75 4071.69   72.62    4375      75    4394      76
    4400      78    4446      81    4568      87    4612      88 4624.22      90
#Mann= 7 ,-1 , 0
       0     .12       0 2601.95     .05       0    2750     .12       0
 3017.26     .05       0 3177.27     .12       0 3942.06     .05       0
 4071.69     .12       0
#XS Ineff= 4 ,-1
       0    2590    81.8    2900    3016    81.8    3350    3866    81.8
    4075 4624.22    81.8
Permanent Ineff=
       F       F       F       F
Bank Sta=2601.95,2750
XS Rating Curve= 0 ,0
Exp/Cntr=0.5,0.3

Type RM Length L Ch R = 1 ,130     ,17,20,114
BEGIN DESCRIPTION:
Stn 16+50
END DESCRIPTION:
#Sta/Elev= 30
       0      90     231      84     282      81     388      78    2415      74
    2546      75 2564.87   73.98    2575   66.53 2622.98   64.69 2674.83   67.27
 2678.45   72.27    2711   73.17 2987.02   71.03 3039.68   69.75 3046.77   65.76
 3052.75   64.97 3081.61    67.9 3098.65   71.37 3147.03   71.09 3928.83   72.65
 3953.31   72.27 3958.57   69.15 3986.92   71.68 4049.33   72.59    4332      74
    4360      75    4380      78    4411      80    4581      88 4592.77      90
#Mann= 7 ,-1 , 0
       0     .12       0 2564.87     .05       0    2711     .12       0
 2987.02     .05       0 3147.03     .12       0 3928.83     .05       0
 4049.33     .12       0
#XS Ineff= 4 ,-1
       0    2550    81.8    2878    2980    81.8    3325    3836    81.8
    4050 4592.77    81.8
Permanent Ineff=
       F       F       F       F
Bank Sta=2564.87,2711
XS Rating Curve= 0 ,0
Exp/Cntr=0.5,0.3

Type RM Length L Ch R = 1 ,120     ,52,40,22
BEGIN DESCRIPTION:
Stn 16+70
END DESCRIPTION:
#Sta/Elev= 30
       0      90     153      85     226      84     253      81     418      78
     595      77    1410      77    1469      76 2551.74   73.68 2560.11   66.22
 2608.77   64.92  2628.7   66.79 2657.91   67.21 2663.09   72.19 2693.21   72.81
 2973.99   70.97 3023.96   69.39 3034.21   64.86 3072.54   69.06  3080.4    70.9
 3133.99   71.12 3943.43   72.09 4018.76   70.19 4044.08   71.52    4362      75
    4383      76    4409      79    4439      80    4494      86 4558.25      90
#Mann= 7 ,-1 , 0
       0     .12       0 2551.74     .05       0 2693.21     .12       0
 2973.99     .05       0 3133.99     .12       0 3943.43     .05       0
 4044.08     .12       0
#XS Ineff= 4 ,-1
       0    2545    81.8    2880    2970    81.8    3329    3805    81.8
    4049 4558.25    81.8
Permanent Ineff=
       F       F       F       F
Bank Sta=2551.74,2693.21
XS Rating Curve= 0 ,0
Exp/Cntr=0.5,0.3

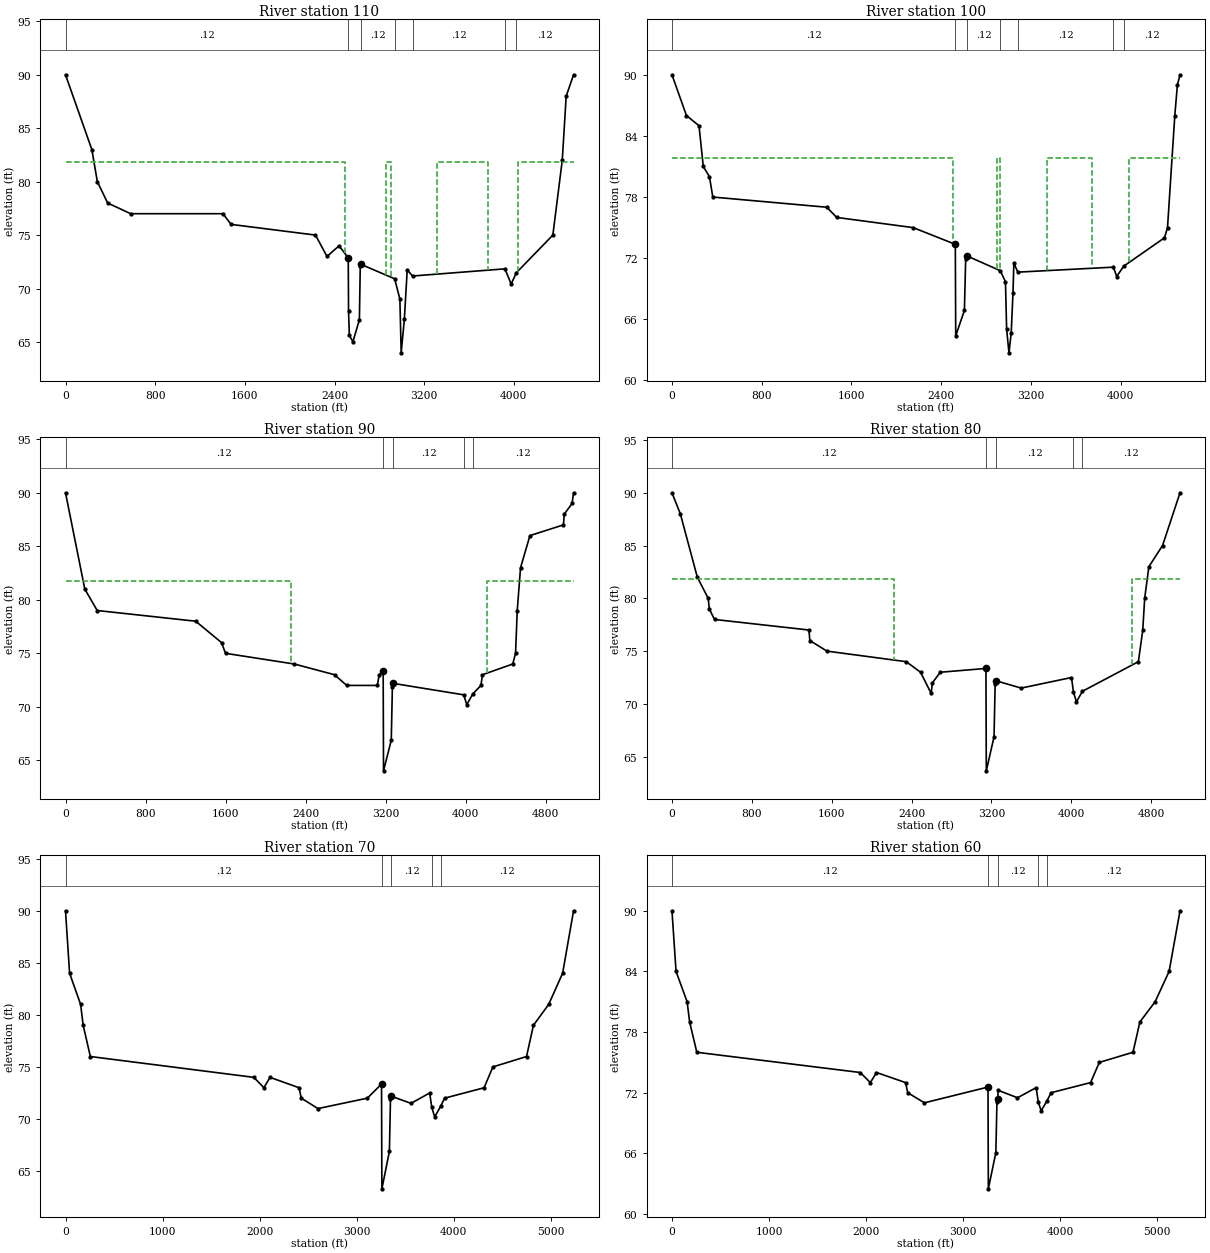
Type RM Length L Ch R = 1 ,110     ,45,40,80
BEGIN DESCRIPTION:
Stn 17+10
END DESCRIPTION:
#Sta/Elev= 30
       0      90     235      83     284      80     376      78     581      77
    1405      77    1477      76    2230      75    2333      73    2441      74
 2522.62   72.86  2525.2   67.88 2532.33   65.62 2564.01   65.01 2622.08   67.08
 2629.64   72.08 2635.86   72.26 2936.66   70.91 2983.21   69.01 2994.77   63.98
 3023.12   67.12 3048.67   71.74 3096.66   71.17  3920.3   71.84 3976.28   70.42
 4021.91   71.47    4348      75    4432      82    4467      88 4532.65      90
#Mann= 7 ,-1 , 0
       0     .12       0 2522.62     .05       0 2635.86     .12       0
 2936.66     .05       0 3096.66     .12       0  3920.3     .05       0
 4021.91     .12       0
#XS Ineff= 4 ,-1
       0    2498    81.8    2863    2900    81.8    3314    3767    81.8
    4033 4532.65    81.8
Permanent Ineff=
       F       F       F       F
Bank Sta=2522.62,2635.86
XS Rating Curve= 0 ,0
Exp/Cntr=0.5,0.3

Type RM Length L Ch R = 1 ,100     ,174,168.67,113.33
BEGIN DESCRIPTION:
Stn 17+50
END DESCRIPTION:
#Sta/Elev= 30
       0      90     129      86     241      85     279      81     334      80
     364      78    1380      77    1468      76    2150      75 2525.65   73.36
  2529.2   64.38 2606.63   66.88 2617.88    71.9 2628.16   72.23  2926.4   70.77
 2972.61   69.69  2982.8   65.06 3003.85   62.71 3023.82   64.67 3039.77   68.62
  3047.3   71.52 3082.57   70.63 3934.43   71.12 3964.38    70.2 4024.82    71.2
    4390      74    4417      75    4482      86    4505      89 4528.44      90
#Mann= 7 ,-1 , 0
       0     .12       0 2525.65     .05       0 2628.16     .12       0
  2926.4     .05       0 3082.57     .12       0 3934.43     .05       0
 4024.82     .12       0
#XS Ineff= 4 ,-1
       0    2504    81.8    2894    2920    81.8    3339    3741    81.8
    4078 4528.44    81.8
Permanent Ineff=
       F       F       F       F
Bank Sta=2525.65,2628.16
XS Rating Curve= 0 ,0
Exp/Cntr=0.5,0.3

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
Type RM Length L Ch R = 1 ,90      ,142.67,173.33,152.67
#Sta/Elev= 30
       0      90     193      81     317      79    1302      78    1560      76
    1600      75    2288      74    2690      73    2812      72    3118      72
    3137      73 3176.35   73.36  3179.9   64.02 3257.33   66.88 3268.58    71.9
 3276.96   72.19  3982.2   71.12 4012.15    70.2 4072.59    71.2    4154      72
    4169      73    4472      74    4500      75    4517      79    4550      83
    4644      86    4979      87    4987      88    5065      89    5080      90
#Mann= 5 ,-1 , 0
       0     .12       0 3176.35     .05       0 3276.96     .12       0
  3982.2     .05       0 4072.59     .12       0
#XS Ineff= 2 ,-1
       0    2258    81.8    4216    5080    81.8
Permanent Ineff=
       F       F
Bank Sta=3176.35,3276.96
XS Rating Curve= 0 ,0
Exp/Cntr=0.5,0.3

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
Type RM Length L Ch R = 1 ,80      ,123,151.5,98.5
#Sta/Elev= 30
       0      90      84      88     254      82     363      80     374      79
     426      78    1372      77    1381      76    1553      75    2347      74
    2490      73    2596      71    2609      72    2688      73 3145.05   73.36
  3148.6   63.66 3226.03   66.88 3237.28    71.9 3245.66   72.19    3498    71.5
    4002    72.5 4021.66   71.12 4051.61    70.2 4112.05    71.2    4672      74
    4716      77    4735      80    4777      83    4914      85    5089      90
#Mann= 5 ,-1 , 0
       0     .12       0 3145.05     .05       0 3245.66     .12       0
 4021.66     .05       0 4112.05     .12       0
#XS Ineff= 2 ,-1
       0    2222    81.8    4608    5089    81.8
Permanent Ineff=
       F       F
Bank Sta=3145.05,3245.66
XS Rating Curve= 0 ,0
Exp/Cntr=0.5,0.3

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
Type RM Length L Ch R = 1 ,70      ,100,200,100
BEGIN DESCRIPTION:
Downstream
END DESCRIPTION:
#Sta/Elev= 30
       0      90      42      84     156      81     182      79     256      76
    1940      74    2044      73    2107      74    2407      73    2429      72
    2601      71    3110      72 3256.05   73.36  3259.6   63.29 3337.03   66.88
 3348.28    71.9 3356.66   72.19    3560    71.5    3752    72.5 3773.64   71.12
 3803.59    70.2 3864.03    71.2    3906      72    4313      73    4403      75
    4750      76    4821      79    4978      81    5122      84 5234.44      90
#Mann= 5 ,-1 , 0
       0     .12       0 3256.05     .05       0 3356.66     .12       0
 3773.64     .05       0 3864.03     .12       0
Bank Sta=3256.05,3356.66
XS Rating Curve= 0 ,0
Exp/Cntr=0.3,0.1

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
Type RM Length L Ch R = 1 ,60      ,100,200,100
BEGIN DESCRIPTION:
Downstream
END DESCRIPTION:
#Sta/Elev= 30
       0      90      42      84     156      81     182      79     256      76
    1940      74    2044      73    2107      74    2407      73    2429      72
    2601      71 3256.05   72.56  3259.6   62.49 3337.03   66.08 3348.28    71.1
 3356.66   71.39 3360.84   72.24    3560    71.5    3752    72.5 3773.64   71.12
 3803.59    70.2 3864.03    71.2    3906      72    4313      73    4403      75
    4750      76    4821      79    4978      81    5122      84 5234.44      90
#Mann= 5 ,-1 , 0
       0     .12       0 3256.05     .05       0 3356.66     .12       0
 3773.64     .05       0 3864.03     .12       0
Bank Sta=3256.05,3356.66
XS Rating Curve= 0 ,0
Exp/Cntr=0.3,0.1

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