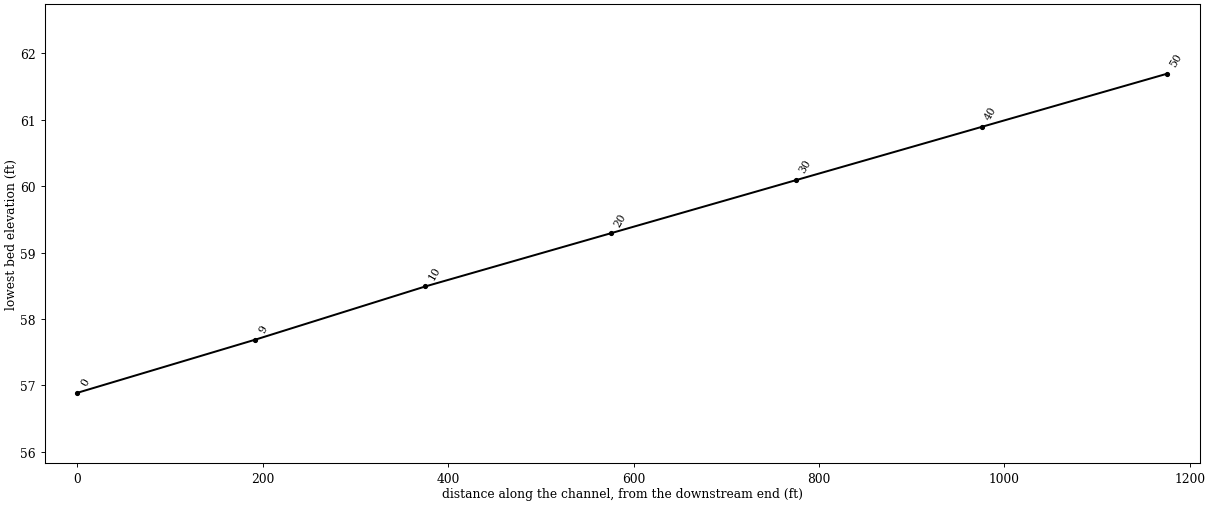
HEC-RAS study S45MultipleBr.prj: S45 Multiple Br

--- S45MultipleBr.g04 (geometry) --- (continued)

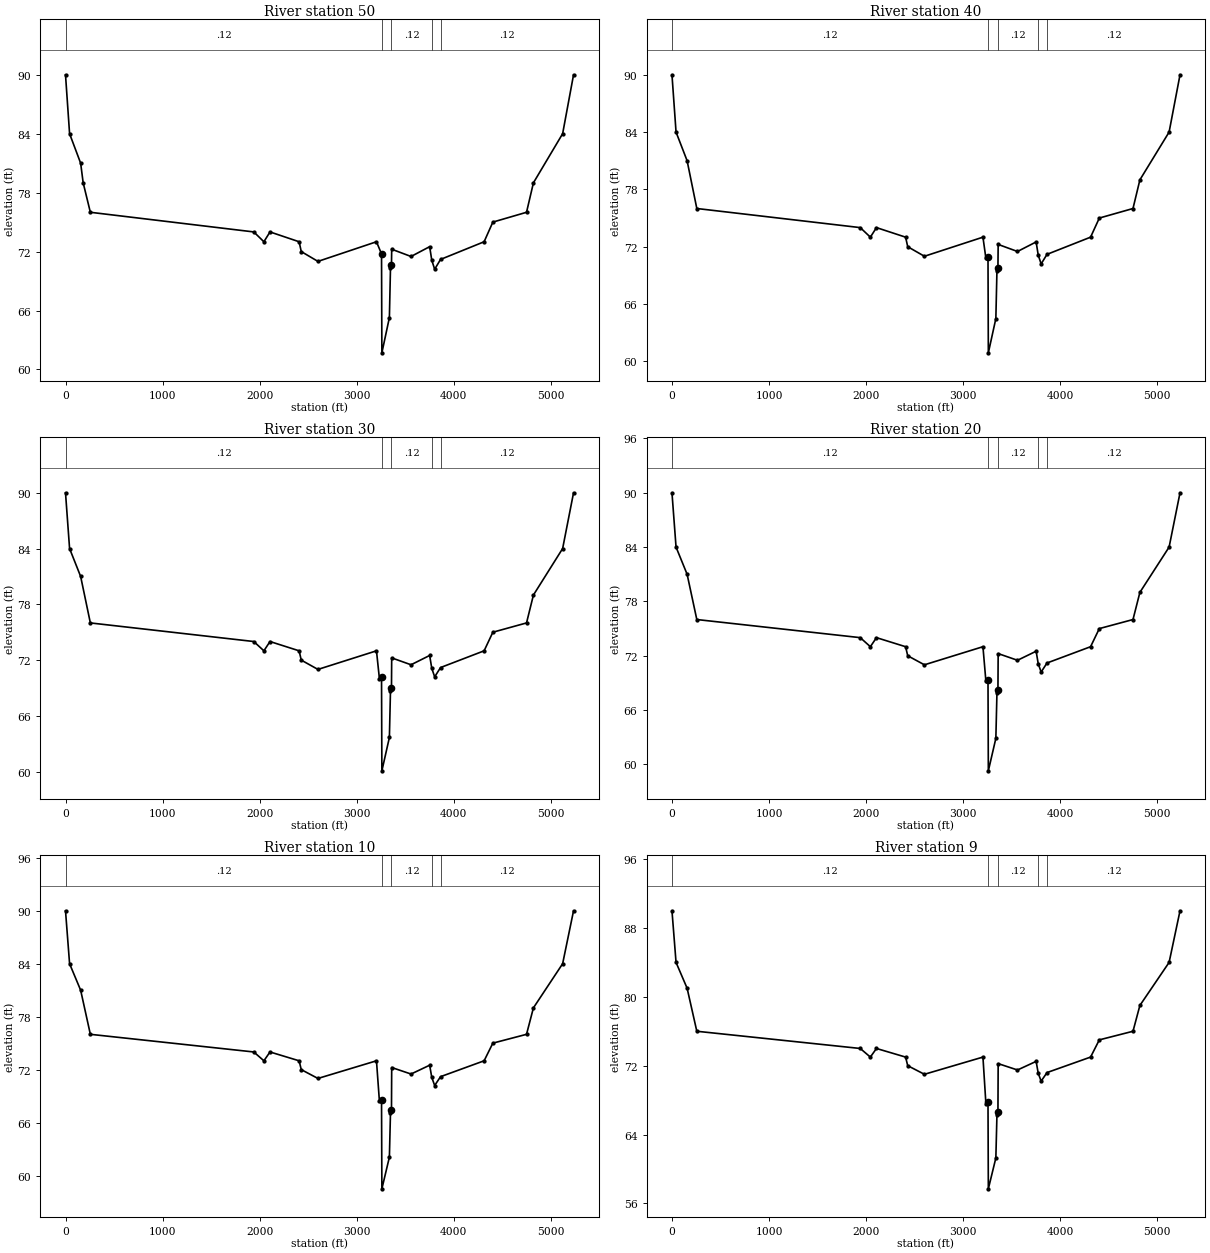
Type RM Length L Ch R = 1 ,50      ,100,200,100
BEGIN DESCRIPTION:
Downstream
END DESCRIPTION:
#Sta/Elev= 30
       0      90      42      84     156      81     182      79     256      76
    1940      74    2044      73    2107      74    2407      73    2429      72
    2601      71    3204      73 3256.05   71.76  3259.6   61.69 3337.03   65.28
 3348.28    70.3 3356.66   70.59 3358.56   70.63 3360.84   72.24    3560    71.5
    3752    72.5 3773.64   71.12 3803.59    70.2 3864.03    71.2    4313      73
    4403      75    4750      76    4821      79    5122      84 5234.44      90
#Mann= 5 ,-1 , 0
       0     .12       0 3256.05     .05       0 3356.66     .12       0
 3773.64     .05       0 3864.03     .12       0
Bank Sta=3256.05,3356.66
XS Rating Curve= 0 ,0
Exp/Cntr=0.3,0.1

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
Type RM Length L Ch R = 1 ,40      ,100,200,100
BEGIN DESCRIPTION:
Downstream
END DESCRIPTION:
#Sta/Elev= 30
       0      90      42      84     156      81     256      76    1940      74
    2044      73    2107      74    2407      73    2429      72    2601      71
    3204      73  3234.4   70.79 3256.05   70.96  3259.6   60.89 3337.03   64.48
 3348.28    69.5 3356.66   69.79 3358.56   69.83 3360.84   72.24    3560    71.5
    3752    72.5 3773.64   71.12 3803.59    70.2 3864.03    71.2    4313      73
    4403      75    4750      76    4821      79    5122      84 5234.44      90
#Mann= 5 ,-1 , 0
       0     .12       0 3256.05     .05       0 3356.66     .12       0
 3773.64     .05       0 3864.03     .12       0
Bank Sta=3256.05,3356.66
XS Rating Curve= 0 ,0
Exp/Cntr=0.3,0.1

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
Type RM Length L Ch R = 1 ,30      ,100,200,100
BEGIN DESCRIPTION:
Downstream
END DESCRIPTION:
#Sta/Elev= 30
       0      90      42      84     156      81     256      76    1940      74
    2044      73    2107      74    2407      73    2429      72    2601      71
    3204      73  3234.4   69.99 3256.05   70.16  3259.6   60.09 3337.03   63.68
 3348.28    68.7 3356.66   68.99 3358.56   69.03 3360.84   72.24    3560    71.5
    3752    72.5 3773.64   71.12 3803.59    70.2 3864.03    71.2    4313      73
    4403      75    4750      76    4821      79    5122      84 5234.44      90
#Mann= 5 ,-1 , 0
       0     .12       0 3256.05     .05       0 3356.66     .12       0
 3773.64     .05       0 3864.03     .12       0
Bank Sta=3256.05,3356.66
XS Rating Curve= 0 ,0
Exp/Cntr=0.3,0.1

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
Type RM Length L Ch R = 1 ,20      ,100,200,100
BEGIN DESCRIPTION:
Downstream
END DESCRIPTION:
#Sta/Elev= 30
       0      90      42      84     156      81     256      76    1940      74
    2044      73    2107      74    2407      73    2429      72    2601      71
    3204      73  3234.4   69.19 3256.05   69.36  3259.6   59.29 3337.03   62.88
 3348.28    67.9 3356.66   68.19 3358.56   68.23 3360.84   72.24    3560    71.5
    3752    72.5 3773.64   71.12 3803.59    70.2 3864.03    71.2    4313      73
    4403      75    4750      76    4821      79    5122      84 5234.44      90
#Mann= 5 ,-1 , 0
       0     .12       0 3256.05     .05       0 3356.66     .12       0
 3773.64     .05       0 3864.03     .12       0
Bank Sta=3256.05,3356.66
XS Rating Curve= 0 ,0
Exp/Cntr=0.3,0.1

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
Type RM Length L Ch R = 1 ,10      ,96.36,183.27,100
#Sta/Elev= 30
       0      90      42      84     156      81     256      76    1940      74
    2044      73    2107      74    2407      73    2429      72    2601      71
    3204      73  3234.4   68.39 3256.05   68.56  3259.6   58.49 3337.03   62.08
 3348.28    67.1 3356.66   67.39 3358.56   67.43 3360.84   72.24    3560    71.5
    3752    72.5 3773.64   71.12 3803.59    70.2 3864.03    71.2    4313      73
    4403      75    4750      76    4821      79    5122      84 5234.44      90
#Mann= 5 ,-1 , 0
       0     .12       0 3256.05     .05       0 3356.66     .12       0
 3773.64     .05       0 3864.03     .12       0
Bank Sta=3256.05,3356.66
XS Rating Curve= 0 ,0
Exp/Cntr=0.3,0.1

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
Type RM Length L Ch R = 1 ,9       ,100,192,100
#Sta/Elev= 30
       0      90      42      84     156      81     256      76    1940      74
    2044      73    2107      74    2407      73    2429      72    2601      71
    3204      73  3234.4   67.59 3256.05   67.76  3259.6   57.69 3337.03   61.28
 3348.28    66.3 3356.66   66.59 3358.56   66.63 3360.84   72.24    3560    71.5
    3752    72.5 3773.64   71.12 3803.59    70.2 3864.03    71.2    4313      73
    4403      75    4750      76    4821      79    5122      84 5234.44      90
#Mann= 5 ,-1 , 0
       0     .12       0 3256.05     .05       0 3356.66     .12       0
 3773.64     .05       0 3864.03     .12       0
Bank Sta=3256.05,3356.66
XS Rating Curve= 0 ,0
Exp/Cntr=0.3,0.1

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
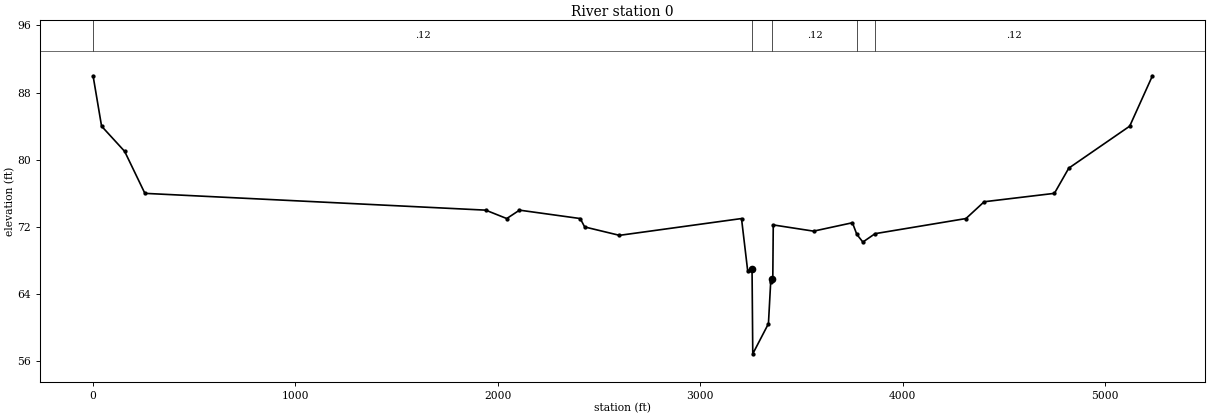
Type RM Length L Ch R = 1 ,0       ,1000,2000,1000
BEGIN DESCRIPTION:
Downstream
END DESCRIPTION:
#Sta/Elev= 30
       0      90      42      84     156      81     256      76    1940      74
    2044      73    2107      74    2407      73    2429      72    2601      71
    3204      73  3234.4   66.79 3256.05   66.96  3259.6   56.89 3337.03   60.48
 3348.28    65.5 3356.66   65.79 3358.56   65.83 3360.84   72.24    3560    71.5
    3752    72.5 3773.64   71.12 3803.59    70.2 3864.03    71.2    4313      73
    4403      75    4750      76    4821      79    5122      84 5234.44      90
#Mann= 5 ,-1 , 0
       0     .12       0 3256.05     .05       0 3356.66     .12       0
 3773.64     .05       0 3864.03     .12       0
Bank Sta=3256.05,3356.66
XS Rating Curve= 0 ,0
Exp/Cntr=0.3,0.1
Stream Node=Little Pee Dee  ,S45             , 0 , 0 ,Upstream end
Stream Node=Little Pee Dee  ,S45             , 0 , 1 ,Downstream end
LCMann Table=0

Chan Stop Cuts=-1
Use User Specified Reach Order=0
Composite Channel Slope=5

--- S45MultipleBr.g01 (geometry) ---

Geom Title=Existing-PW
Program Version=5.01

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
River Reach=Little Pee Dee  ,S45

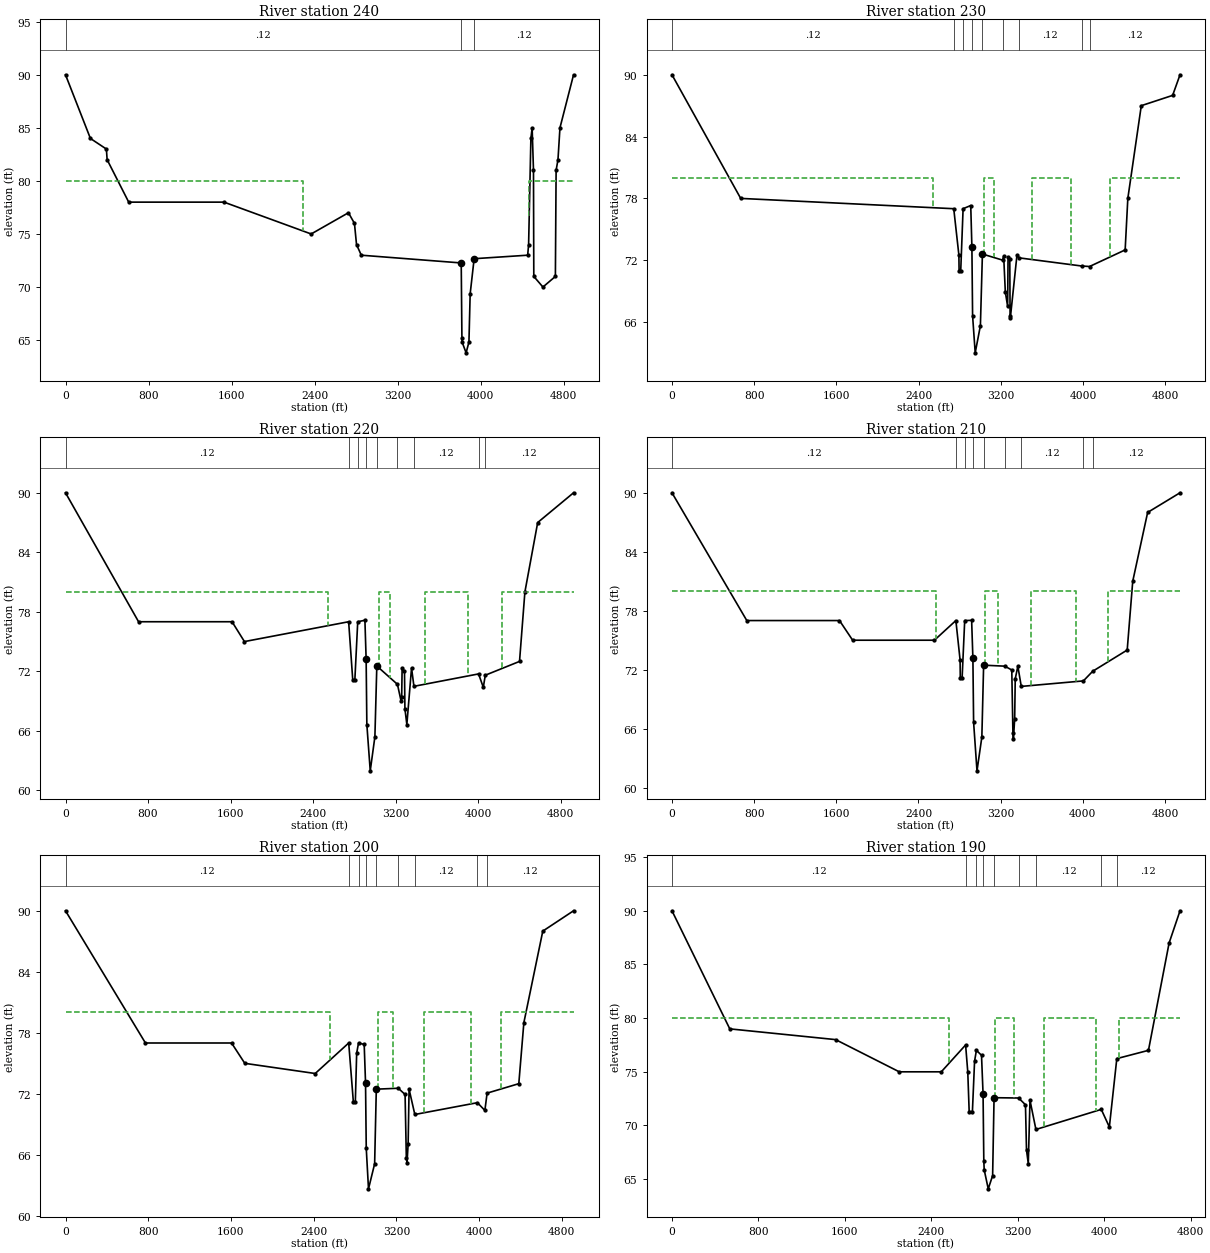
Type RM Length L Ch R = 1 ,240     ,18.67,179,27.89
#Sta/Elev= 30
       0      90     240      84     394      83     401      82     609      78
    1527      78    2367      75    2726      77    2784      76    2804      74
    2850      73 3812.72   72.27 3819.51   65.16 3820.95   64.82 3859.85    63.8
 3887.08   64.82 3898.94   69.36 3937.15   72.67    4453      73    4462      74
    4484      84    4496      85    4509      81    4512      71    4600      70
    4720      71    4727      81    4745      82    4764      85    4895      90
#Mann= 3 , 0 , 0
       0     .12       0 3812.72     .05       0 3937.15     .12       0
#XS Ineff= 2 ,-1
       0    2284      80    4468    4895      80
Permanent Ineff=
       F       F
Bank Sta=3812.72,3937.15
XS Rating Curve= 0 ,0
Exp/Cntr=0.5,0.3

Type RM Length L Ch R = 1 ,230     ,8,10,20
BEGIN DESCRIPTION:
Stn 12+90
END DESCRIPTION:
#Sta/Elev= 30
       0      90   668.8      78    2742      77    2792    72.5    2794      71
    2810      71    2833      77 2907.37   77.31 2918.64   73.26 2925.36   66.62
 2950.79   63.01 3001.36   65.65 3021.02    72.6 3217.03   72.01 3228.08   72.37
 3243.87   68.92 3266.36   67.52 3270.55    72.3 3287.33   72.11 3290.27   66.54
  3293.1   66.43 3357.36   72.51 3377.02   72.23 3985.41   71.44 4063.55   71.39
    4410      73    4436      78    4567      87    4872      88 4943.86      90
#Mann= 9 ,-1 , 0
       0     .12       0    2742     .05       0    2833     .12       0
 2918.64     .05       0 3021.02     .12       0 3217.03     .05       0
 3377.02     .12       0 3985.41     .05       0 4063.55     .12       0
#XS Ineff= 4 ,-1
       0    2540      80    3040    3129      80    3508    3880      80
    4260 4943.86      80
Permanent Ineff=
       F       F       F       F
Bank Sta=2918.64,3021.02
XS Rating Curve= 0 ,0
Exp/Cntr=0.5,0.3

Type RM Length L Ch R = 1 ,220     ,6,10,10
BEGIN DESCRIPTION:
Stn 13+00
END DESCRIPTION:
#Sta/Elev= 30
       0      90     708      77    1614      77    1734      75    2744      77
    2784    71.1    2804    71.1    2832      77 2901.64   77.15 2913.56    73.2
 2920.34   66.64 2953.23   61.97  2998.4   65.41 3016.98   72.54 3216.92   70.69
  3252.6   68.98 3257.85   69.37 3262.23    72.3 3285.22   72.02 3289.36   68.22
 3308.06   66.64 3353.49   72.34 3376.68   70.49 4003.07   71.74 4048.96   70.39
 4068.31   71.61    4400      73    4452      80    4576      87 4923.55      90
#Mann= 9 ,-1 , 0
       0     .12       0    2744     .05       0    2832     .12       0
 2913.56     .05       0 3016.98     .12       0 3216.92     .05       0
 3376.68     .12       0 4003.07     .05       0 4068.31     .12       0
#XS Ineff= 4 ,-1
       0    2548      80    3034    3144      80    3485    3898      80
    4234 4923.55      80
Permanent Ineff=
       F       F       F       F
Bank Sta=2913.56,3016.98
XS Rating Curve= 0 ,0
Exp/Cntr=0.5,0.3

Type RM Length L Ch R = 1 ,210     ,8,10,10
BEGIN DESCRIPTION:
Stn 13+10
END DESCRIPTION:
#Sta/Elev= 30
       0      90   728.5      77    1631      77    1759      75    2555      75
    2764      77    2805      73    2807    71.2    2825    71.2    2850      77
 2917.46   77.02 2929.82   73.14 2936.64   66.65 2969.59   61.71 3016.91   65.14
 3034.24   72.46 3240.69   72.36 3308.33   71.97 3319.38   65.58 3324.41   64.95
 3336.43      67 3342.03   71.07 3367.41   72.36 3400.68    70.3 4005.49   70.86
 4095.98   71.84    4432      74    4486      81    4631      88 4946.23      90
#Mann= 9 ,-1 , 0
       0     .12       0    2764     .05       0    2850     .12       0
 2929.82     .05       0 3034.24     .12       0 3240.69     .05       0
 3400.68     .12       0 4005.49     .05       0 4095.98     .12       0
#XS Ineff= 4 ,-1
       0    2573      80    3048    3178      80    3498    3931      80
    4247 4946.23      80
Permanent Ineff=
       F       F       F       F
Bank Sta=2929.82,3034.24
XS Rating Curve= 0 ,0
Exp/Cntr=0.5,0.3

Type RM Length L Ch R = 1 ,200     ,15,20,50
BEGIN DESCRIPTION:
Stn 13+20
END DESCRIPTION:
#Sta/Elev= 30
       0      90     773      77    1606      77    1734      75    2415      74
    2739      77    2784    71.2    2803    71.2    2816      76    2834      77
 2888.71   76.86 2901.71   73.08 2908.59   66.66 2930.34   62.66 2989.71   65.12
  3005.9   72.46 3218.38   72.55 3284.13   71.94 3296.25   65.73 3302.91   65.22
 3313.75   67.09 3322.86   72.46 3378.38   69.97 3983.49   71.13 4055.94   70.37
 4077.34   72.07    4384      73    4433      79    4616      88 4913.48      90
#Mann= 9 ,-1 , 0
       0     .12       0    2739     .05       0    2834     .12       0
 2901.71     .05       0  3005.9     .12       0 3218.38     .05       0
 3378.38     .12       0 3983.49     .05       0 4077.34     .12       0
#XS Ineff= 4 ,-1
       0    2558      80    3019    3165      80    3464    3918      80
    4213 4913.48      80
Permanent Ineff=
       F       F       F       F
Bank Sta=2901.71,3005.9
XS Rating Curve= 0 ,0
Exp/Cntr=0.5,0.3

Type RM Length L Ch R = 1 ,190     ,8,10,10
BEGIN DESCRIPTION:
Stn 13+40
END DESCRIPTION:
#Sta/Elev= 30
       0      90     535      79    1514      78    2103      75    2492      75
    2717    77.5    2737      75    2750    71.3    2780    71.3    2800      76
    2817      77  2864.2   76.54 2878.48   72.95 2885.48   66.69 2889.15   65.87
 2926.42    64.1 2967.08   65.33 2980.28   72.59  3207.6   72.56  3270.9   71.93
 3280.47   67.71 3296.98   66.45 3312.77   72.35  3367.6   69.63 3972.36    71.5
 4047.17   69.86 4116.08   76.23    4409      77    4600      87 4700.93      90
#Mann= 9 ,-1 , 0
       0     .12       0    2717     .05       0    2817     .12       0
 2878.48     .05       0 2980.28     .12       0  3207.6     .05       0
  3367.6     .12       0 3972.36     .05       0 4116.08     .12       0
#XS Ineff= 4 ,-1
       0    2560      80    2993    3166      80    3440    3919      80
    4139 4700.93      80
Permanent Ineff=
       F       F       F       F
Bank Sta=2878.48,2980.28
XS Rating Curve= 0 ,0
Exp/Cntr=0.5,0.3

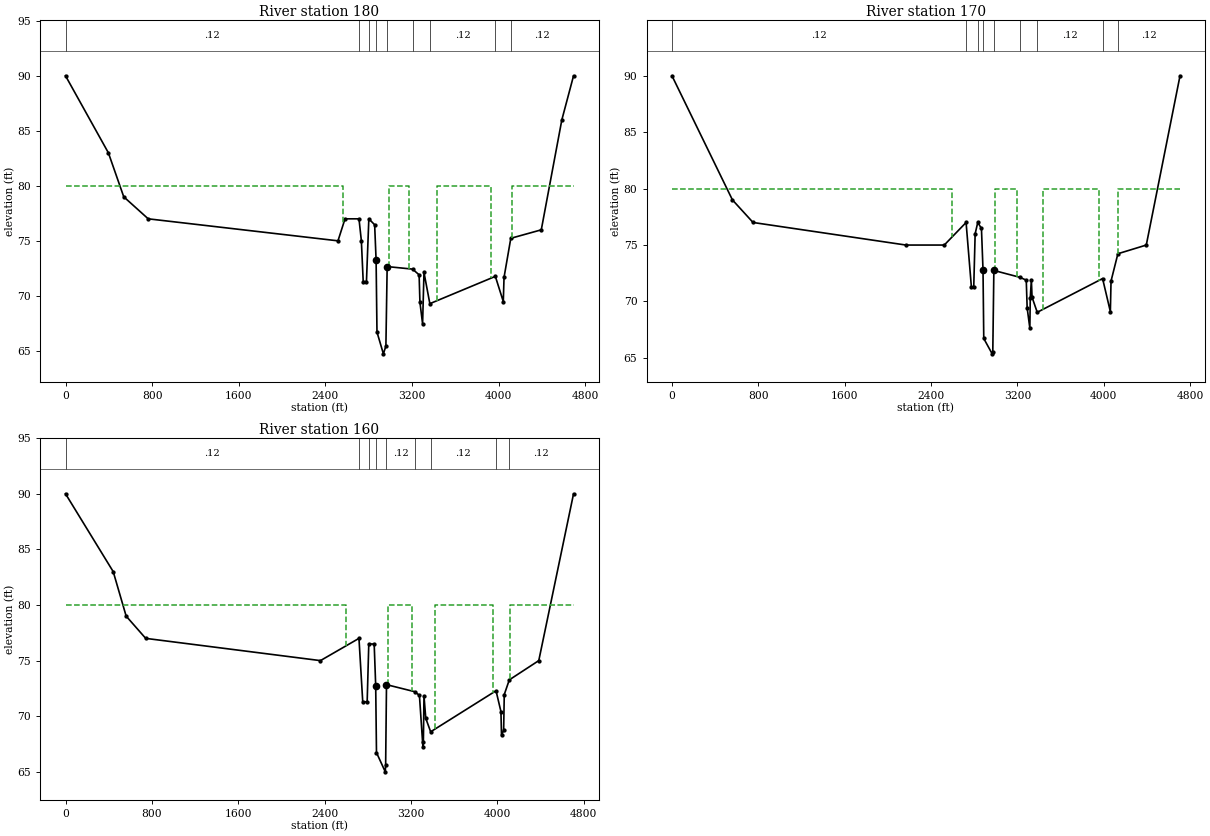
Type RM Length L Ch R = 1 ,180     ,9,10,10
BEGIN DESCRIPTION:
Stn 13+50
END DESCRIPTION:
#Sta/Elev= 30
       0      90     396      83     538      79     764      77    2517      75
    2582      77    2711      77    2733      75    2750    71.3    2780    71.3
    2802      77 2855.69   76.46 2869.15   73.23 2877.21   66.71 2936.37   64.73
 2959.62   65.44 2971.31   72.66 3205.61   72.43 3266.47   71.91 3273.94   69.42
 3298.54   67.45  3311.4   72.13 3365.61   69.29 3970.69   71.77 4044.06   69.48
  4050.8   71.67 4113.38   75.23    4395      76    4585      86 4693.01      90
#Mann= 9 ,-1 , 0
       0     .12       0    2711     .05       0    2802     .12       0
 2869.15     .05       0 2971.31     .12       0 3205.61     .05       0
 3365.61     .12       0 3970.69     .05       0 4113.38     .12       0
#XS Ineff= 4 ,-1
       0    2566      80    2984    3173      80    3428    3927      80
    4125 4693.01      80
Permanent Ineff=
       F       F       F       F
Bank Sta=2869.15,2971.31
XS Rating Curve= 0 ,0
Exp/Cntr=0.5,0.3

Type RM Length L Ch R = 1 ,170     ,10,10,10
BEGIN DESCRIPTION:
Stn 13+60
END DESCRIPTION:
#Sta/Elev= 30
       0      90     560      79     751      77    2167      75    2522      75
    2724      77    2773    71.3    2795    71.3    2808      76    2832      77
 2866.34   76.47 2880.74   72.81 2887.76   66.72 2965.58   65.36 2971.42   65.54
 2981.26   72.75  3222.9   72.14 3281.31   71.89 3289.71   69.43  3314.6   67.63
 3318.49   70.33 3328.69   71.93 3335.07   70.38  3382.9   69.04  3988.3   72.03
 4060.25    69.1 4066.53   71.81 4129.98   74.23    4393      75 4705.39      90
#Mann= 9 ,-1 , 0
       0     .12       0    2724     .05       0    2832     .12       0
 2880.74     .05       0 2981.26     .12       0  3222.9     .05       0
  3382.9     .12       0  3988.3     .05       0 4129.98     .12       0
#XS Ineff= 4 ,-1
       0    2592      80    2994    3200      80    3433    3953      80
    4131 4705.39      80
Permanent Ineff=
       F       F       F       F
Bank Sta=2880.74,2981.26
XS Rating Curve= 0 ,0
Exp/Cntr=0.5,0.3

Type RM Length L Ch R = 1 ,160     ,129.99,110.01,24.99
BEGIN DESCRIPTION:
Stn 13+70
END DESCRIPTION:
#Sta/Elev= 30
       0      90     442      83     562      79     743      77    2362      75
    2719      77    2754    71.3    2795    71.3    2810    76.5    2860   76.49
 2874.04   72.74 2881.32   66.73 2962.82      65 2966.23   65.64 2974.12   72.84
 3233.83   72.21  3279.2   71.88 3311.71    67.2 3315.76   67.66  3321.4   71.82
 3338.06   69.81 3383.23    68.6 3988.94   72.29 4034.42   70.42 4039.66    68.3
 4059.44   68.72 4065.28   71.95 4112.02   73.27    4385      75  4707.2      90
#Mann= 9 ,-1 , 0
       0     .12       0    2719     .05       0    2810     .12       0
 2874.04     .05       0 2974.12     .12       0 3233.83     .05       0
 3383.23     .12       0 3988.94     .05       0 4112.02     .12       0
#XS Ineff= 4 ,-1
       0    2601      80    2988    3210      80    3422    3963      80
    4123  4707.2      80
Permanent Ineff=
       F       F       F       F
Bank Sta=2874.04,2974.12
XS Rating Curve= 0 ,0
Exp/Cntr=0.5,0.3