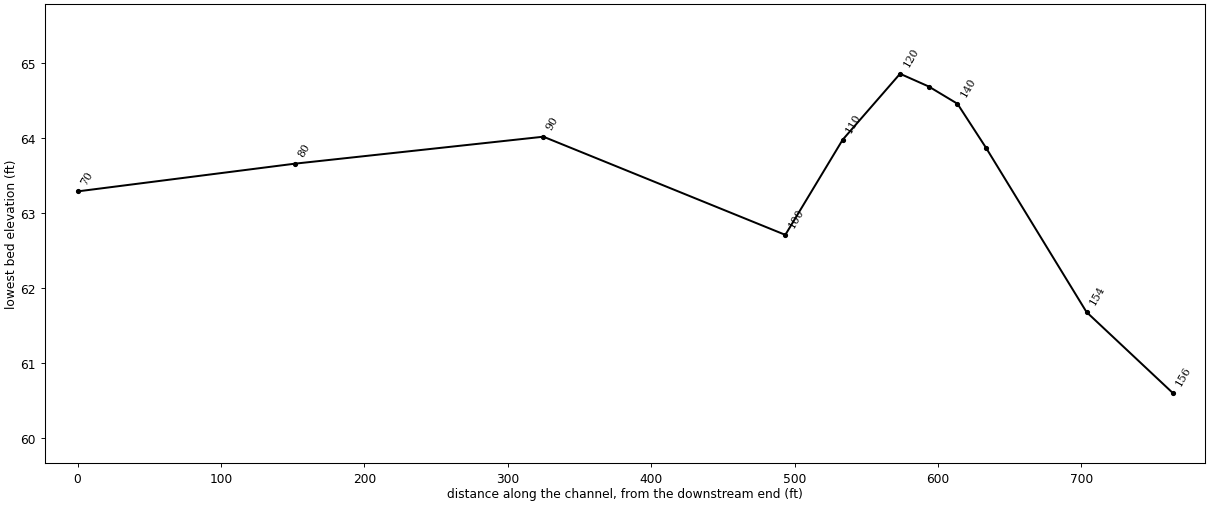
HEC-RAS study S45MultipleBr.prj: S45 Multiple Br

--- S45MultipleBr.g01 (geometry) --- (continued)

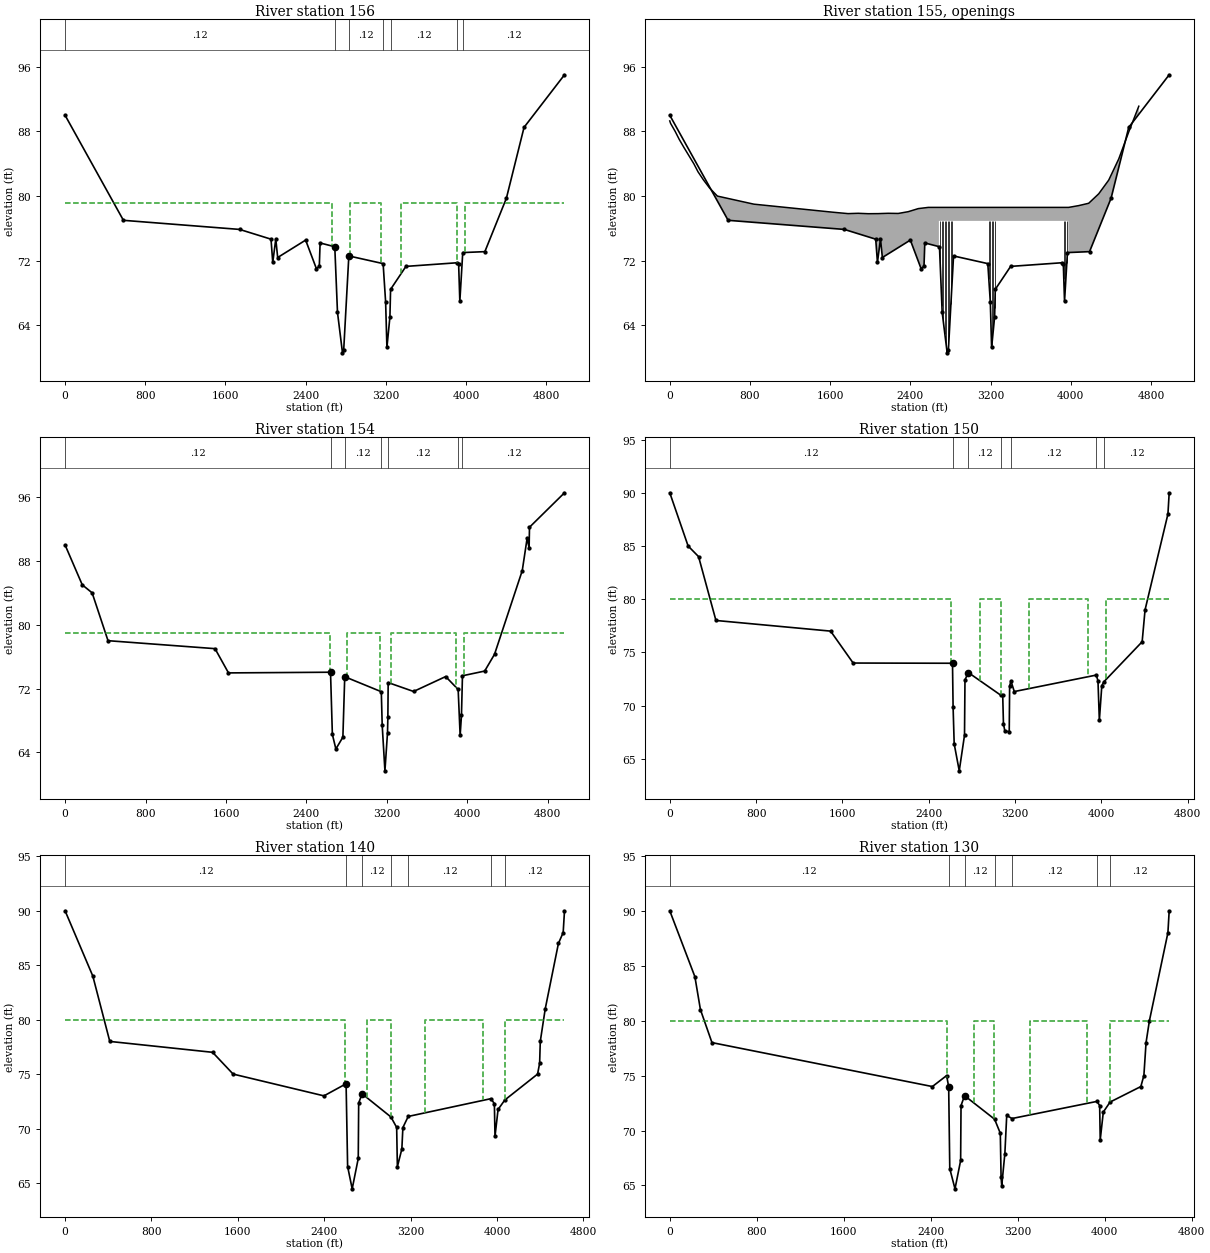
Type RM Length L Ch R = 1 ,156     ,60,60,60
BEGIN DESCRIPTION:
Bridge - Upstream
END DESCRIPTION:
#Sta/Elev= 30
       0      90     582      77 1741.06 75.8743 2054.45 74.6666 2071.79 71.7957
 2102.06 74.6859 2120.88 72.3984 2399.79 74.5524 2507.24 71.0181 2536.19 71.3033
 2544.06    74.2 2690.58   73.73 2717.54 65.6107 2767.44 60.6025 2779.51 60.9536
 2830.78 72.5917 3172.78 71.6429 3197.71 66.8991 3210.64 61.2638 3240.62 65.0586
 3247.21 68.4574 3400.53    71.3 3913.63 71.7514 3926.05 71.6037 3938.04  66.967
 3967.04 73.0092 4187.68 73.1239 4402.62 79.7382 4578.71 88.5063 4982.15 95.0095
#Mann= 7 ,-1 , 0
       0     .12       0 2690.58     .05       0 2830.78     .12       0
 3172.78     .05       0 3247.21     .12       0 3913.63     .05       0
 3967.04     .12       0
#XS Ineff= 4 ,-1
       0    2660    79.1    2839    3154    79.1    3350    3905    79.1
    3994 4982.15    79.1
Permanent Ineff=
       F       F       F       F
Bank Sta=2690.58,2830.78
XS Rating Curve= 0 ,0
Exp/Cntr=0.5,0.3

Type RM Length L Ch R = 4 ,155     ,,,
Bridge Culvert--1,0,-1,-1, 0
Deck Dist Width WeirC Skew NumUp NumDn MinLoCord MaxHiCord MaxSubmerge Is_Ogee
15,30,2.6,0, 55, 50, , , 0.98, 0, 0,0,,
       0       8      54      95     142     191     240     282     336     397
     475     839    1630    1779    1879    1979    2079    2179    2279    2379
    2479    2579  2684.8  2684.8  2834.8  2834.8    2879    2979    3079  3167.8
  3167.8  3167.8  3257.8  3257.8    3279    3329    3379    3429    3479    3579
    3679    3779    3879  3915.8  3915.8  3975.8  3975.8    3979    4079    4179
    4279    4379    4479    4579    4679
    89.3      89      88      87      86      85      84      83      82      81
      80      79      78   77.83   77.87   77.82   77.83   77.87   77.85   78.07
   78.45    78.6    78.6    78.6    78.6    78.6    78.6    78.6    78.6    78.6
    78.6    78.6    78.6    78.6    78.6    78.6    78.6    78.6    78.6    78.6
    78.6    78.6    78.6    78.6    78.6    78.6    78.6    78.6   78.82   79.11
   80.28   81.98    84.6   87.95   91.12
                                                                                
                                                                                
                           76.93   76.93
           76.93   76.93
                                   76.93   76.93
                                        
     240     282     336     397     475     839    1630    1779    1879    1979
    2079    2179    2279    2379    2479    2579  2635.3  2635.3  2785.3  2785.3
    2879    2979    3079  3142.8  3142.8  3232.8  3232.8    3279    3329    3379
    3429    3479    3579    3679    3779    3879  3899.9  3899.9  3959.9  3959.9
    3979    4079    4179    4279    4379    4479    4579    4679    4779    4879
      84      83      82      81      80      79      78   77.83   77.87   77.82
   77.83   77.87   77.85   78.07   78.45    78.6    78.6    78.6    78.6    78.6
    78.6    78.6    78.6    78.6    78.6    78.6    78.6    78.6    78.6    78.6
    78.6    78.6    78.6    78.6    78.6    78.6    78.6    78.6    78.6    78.6
    78.6   78.82   79.11   80.28   81.98    84.6   87.95   91.12   95.31   95.08
                                                                                
                                                           76.93   76.93
                                   76.93   76.93
                                                           76.93   76.93
                                                                                
Pier Skew, UpSta & Num, DnSta & Num=  ,2699.8, 2 ,2650.3, 2 , 0 , 0 , 0 ,,
    1.17    1.17
      60    78.6
    1.17    1.17
      60    78.6
Pier Skew, UpSta & Num, DnSta & Num=  ,2714.8, 2 ,2665.3, 2 , 0 , 0 , 0 ,,
    1.17    1.17
      60    78.6
    1.17    1.17
      60    78.6
Pier Skew, UpSta & Num, DnSta & Num=  ,2729.8, 2 ,2680.3, 2 , 0 , 0 , 0 ,,
    1.17    1.17
      60    78.6
    1.17    1.17
      60    78.6
Pier Skew, UpSta & Num, DnSta & Num=  ,2744.8, 2 ,2695.3, 2 , 0 , 0 , 0 ,,
    1.17    1.17
      60    78.6
    1.17    1.17
      60    78.6
Pier Skew, UpSta & Num, DnSta & Num=  ,2759.8, 2 ,2710.3, 2 , 0 , 0 , 0 ,,
    1.17    1.17
      60    78.6
    1.17    1.17
      60    78.6
Pier Skew, UpSta & Num, DnSta & Num=  ,2774.8, 2 ,2725.3, 2 , 0 , 0 , 0 ,,
    1.17    1.17
      60    78.6
    1.17    1.17
      60    78.6
Pier Skew, UpSta & Num, DnSta & Num=  ,2789.8, 2 ,2740.3, 2 , 0 , 0 , 0 ,,
    1.17    1.17
      60    78.6
    1.17    1.17
      60    78.6
Pier Skew, UpSta & Num, DnSta & Num=  ,2804.8, 2 ,2755.3, 2 , 0 , 0 , 0 ,,
    1.17    1.17
      60    78.6
    1.17    1.17
      60    78.6
Pier Skew, UpSta & Num, DnSta & Num=  ,2819.8, 2 ,2770.3, 2 , 0 , 0 , 0 ,,
    1.17    1.17
      60    78.6
    1.17    1.17
      60    78.6
Pier Skew, UpSta & Num, DnSta & Num=  ,3182.8, 2 ,3157.8, 2 , 0 , 0 , 0 ,,
    1.17    1.17
      60    78.6
    1.17    1.17
      60    78.6
Pier Skew, UpSta & Num, DnSta & Num=  ,3197.8, 2 ,3172.8, 2 , 0 , 0 , 0 ,,
    1.17    1.17
      60    78.6
    1.17    1.17
      60    78.6
Pier Skew, UpSta & Num, DnSta & Num=  ,3212.8, 2 ,3187.8, 2 , 0 , 0 , 0 ,,
    1.17    1.17
      60    78.6
    1.17    1.17
      60    78.6
Pier Skew, UpSta & Num, DnSta & Num=  ,3227.8, 2 ,3202.8, 2 , 0 , 0 , 0 ,,
    1.17    1.17
      60    78.6
    1.17    1.17
      60    78.6
Pier Skew, UpSta & Num, DnSta & Num=  ,3242.8, 2 ,3217.8, 2 , 0 , 0 , 0 ,,
    1.17    1.17
      60    78.6
    1.17    1.17
      60    78.6
Pier Skew, UpSta & Num, DnSta & Num=  ,3930.8, 2 ,3914.9, 2 , 0 , 0 , 0 ,,
    1.17    1.17
      60    78.6
    1.17    1.17
      60    78.6
Pier Skew, UpSta & Num, DnSta & Num=  ,3945.8, 2 ,3929.9, 2 , 0 , 0 , 0 ,,
    1.17    1.17
      60    78.6
    1.17    1.17
      60    78.6
Pier Skew, UpSta & Num, DnSta & Num=  ,3960.8, 2 ,3944.8, 2 , 0 , 0 , 0 ,,
    1.17    1.17
      60    78.6
    1.17    1.17
      60    78.6
Abutment Skew #Up #Dn= , 2 , 2
  2684.8  2686.8
   76.93      60
  2635.3  2637.3
   76.93      60
Abutment Skew #Up #Dn= , 2 , 2
  2832.8  2834.8
      60   76.93
  2783.3  2785.3
      60   76.93
Abutment Skew #Up #Dn= , 2 , 2
  3167.8  3169.8
   76.93      60
  3142.8  3144.8
   76.93      60
Abutment Skew #Up #Dn= , 2 , 2
  3255.8  3257.8
      60   76.93
  3230.8  3232.8
      60   76.93
Abutment Skew #Up #Dn= , 2 , 2
  3915.8  3917.8
   76.93      60
  3899.9  3901.9
   76.93      60
Abutment Skew #Up #Dn= , 2 , 2
  3973.8  3975.8
      60   76.93
  3957.9  3959.9
      60   76.93
BR Coef=-1 , 0 , 0 ,, 0 ,,,0.8,0,,0,
WSPro=,,,, 1 ,,,, 0 ,,,, 0 ,,,,-1 ,-1 ,-1 , 0 , 0 , 0 , 0 , 0
BC Mult= 3 ,0,3095,0,3045.5
BC Mult= 3 ,2900,3700,2850.5,3650.5
BC Mult= 3 ,3400,4982.15,3350.5,4966.11
BC Design=,, 0 ,, 0 ,,,,,,
BC Use User HTab Curves=0
BC User HTab FreeFlow(D)= 0

Type RM Length L Ch R = 1 ,154     ,5,70,35
BEGIN DESCRIPTION:
Bridge - Downstream
END DESCRIPTION:
#Sta/Elev= 30
       0      90     171      85     269      84     427      78    1491      77
 1624.95 73.9596 2639.55 74.0448 2657.88 66.2491 2692.74 64.4206 2762.43 65.9018
 2780.89 73.4811 3144.53 71.6023 3153.45 67.3865 3180.54   61.68 3206.25 66.4675
 3209.74 68.3821 3212.84 72.7469 3465.52 71.6316 3784.49    73.5 3908.73  71.881
 3928.43 66.1158  3941.6 68.6294 3951.49    73.6  4172.4 74.1905 4270.42 76.2945
 4546.17 86.7895 4594.39 90.8314 4614.24 89.6382 4618.07 92.2247 4966.11 96.5451
#Mann= 7 ,-1 , 0
       0     .12       0 2639.55     .05       0 2780.89     .12       0
 3144.53     .05       0 3212.84     .12       0 3908.73     .05       0
 3951.49     .12       0
#XS Ineff= 4 ,-1
       0    2633      79    2807    3135      79    3241    3890      79
    3965 4966.11      79
Permanent Ineff=
       F       F       F       F
Bank Sta=2639.55,2780.89
XS Rating Curve= 0 ,0
Exp/Cntr=0.5,0.3

Type RM Length L Ch R = 1 ,150     ,16,20,18
BEGIN DESCRIPTION:
Stn 16+10
END DESCRIPTION:
#Sta/Elev= 30
       0      90     170      85     267      84     428      78    1491      77
    1700      74 2620.97   73.98 2626.37    69.9 2636.56   66.41 2683.42   63.87
 2732.31   67.22 2736.61   72.41    2767   73.11 3072.25   70.95  3086.5   70.96
 3093.21   68.29 3105.88   67.63 3146.86   67.54 3150.57   71.84  3162.9   72.31
  3193.6   71.32 3954.19   72.87 3969.57   72.32 3982.25   68.61 4005.13   71.88
 4026.35   72.26    4379      76    4406      79    4618      88 4629.68      90
#Mann= 7 ,-1 , 0
       0     .12       0 2620.97     .05       0    2767     .12       0
 3072.25     .05       0  3162.9     .12       0 3954.19     .05       0
 4026.35     .12       0
#XS Ineff= 4 ,-1
       0    2607      80    2880    3072      80    3332    3877      80
    4046 4629.68      80
Permanent Ineff=
       F       F       F       F
Bank Sta=2620.97,2767
XS Rating Curve= 0 ,0
Exp/Cntr=0.5,0.3

Type RM Length L Ch R = 1 ,140     ,18,20,10
BEGIN DESCRIPTION:
Stn 16+30
END DESCRIPTION:
#Sta/Elev= 30
       0      90     257      84     414      78    1366      77    1556      75
    2397      73 2601.95   74.11 2616.15   66.51  2658.4   64.46 2714.57   67.25
 2718.53   72.34    2750   73.19 3017.26   71.06 3070.21    70.1 3076.84   66.49
 3118.23   68.12 3127.89   70.09 3177.27   71.11 3942.06   72.74 3974.94   72.29
 3980.73   69.28 4009.21   71.75 4071.69   72.62    4375      75    4394      76
    4400      78    4446      81    4568      87    4612      88 4624.22      90
#Mann= 7 ,-1 , 0
       0     .12       0 2601.95     .05       0    2750     .12       0
 3017.26     .05       0 3177.27     .12       0 3942.06     .05       0
 4071.69     .12       0
#XS Ineff= 4 ,-1
       0    2593      80    2800    3016      80    3337    3866      80
    4075 4624.22      80
Permanent Ineff=
       F       F       F       F
Bank Sta=2601.95,2750
XS Rating Curve= 0 ,0
Exp/Cntr=0.5,0.3

Type RM Length L Ch R = 1 ,130     ,17,20,114
BEGIN DESCRIPTION:
Stn 16+50
END DESCRIPTION:
#Sta/Elev= 30
       0      90     231      84     282      81     388      78    2415      74
    2546      75 2564.87   73.98    2575   66.53 2622.98   64.69 2674.83   67.27
 2678.45   72.27    2711   73.17 2987.02   71.03 3039.68   69.75 3046.77   65.76
 3052.75   64.97 3081.61    67.9 3098.65   71.37 3147.03   71.09 3928.83   72.65
 3953.31   72.27 3958.57   69.15 3986.92   71.68 4049.33   72.59    4332      74
    4360      75    4380      78    4411      80    4581      88 4592.77      90
#Mann= 7 ,-1 , 0
       0     .12       0 2564.87     .05       0    2711     .12       0
 2987.02     .05       0 3147.03     .12       0 3928.83     .05       0
 4049.33     .12       0
#XS Ineff= 4 ,-1
       0    2550      80    2800    2980      80    3313    3836      80
    4050 4592.77      80
Permanent Ineff=
       F       F       F       F
Bank Sta=2564.87,2711
XS Rating Curve= 0 ,0
Exp/Cntr=0.5,0.3

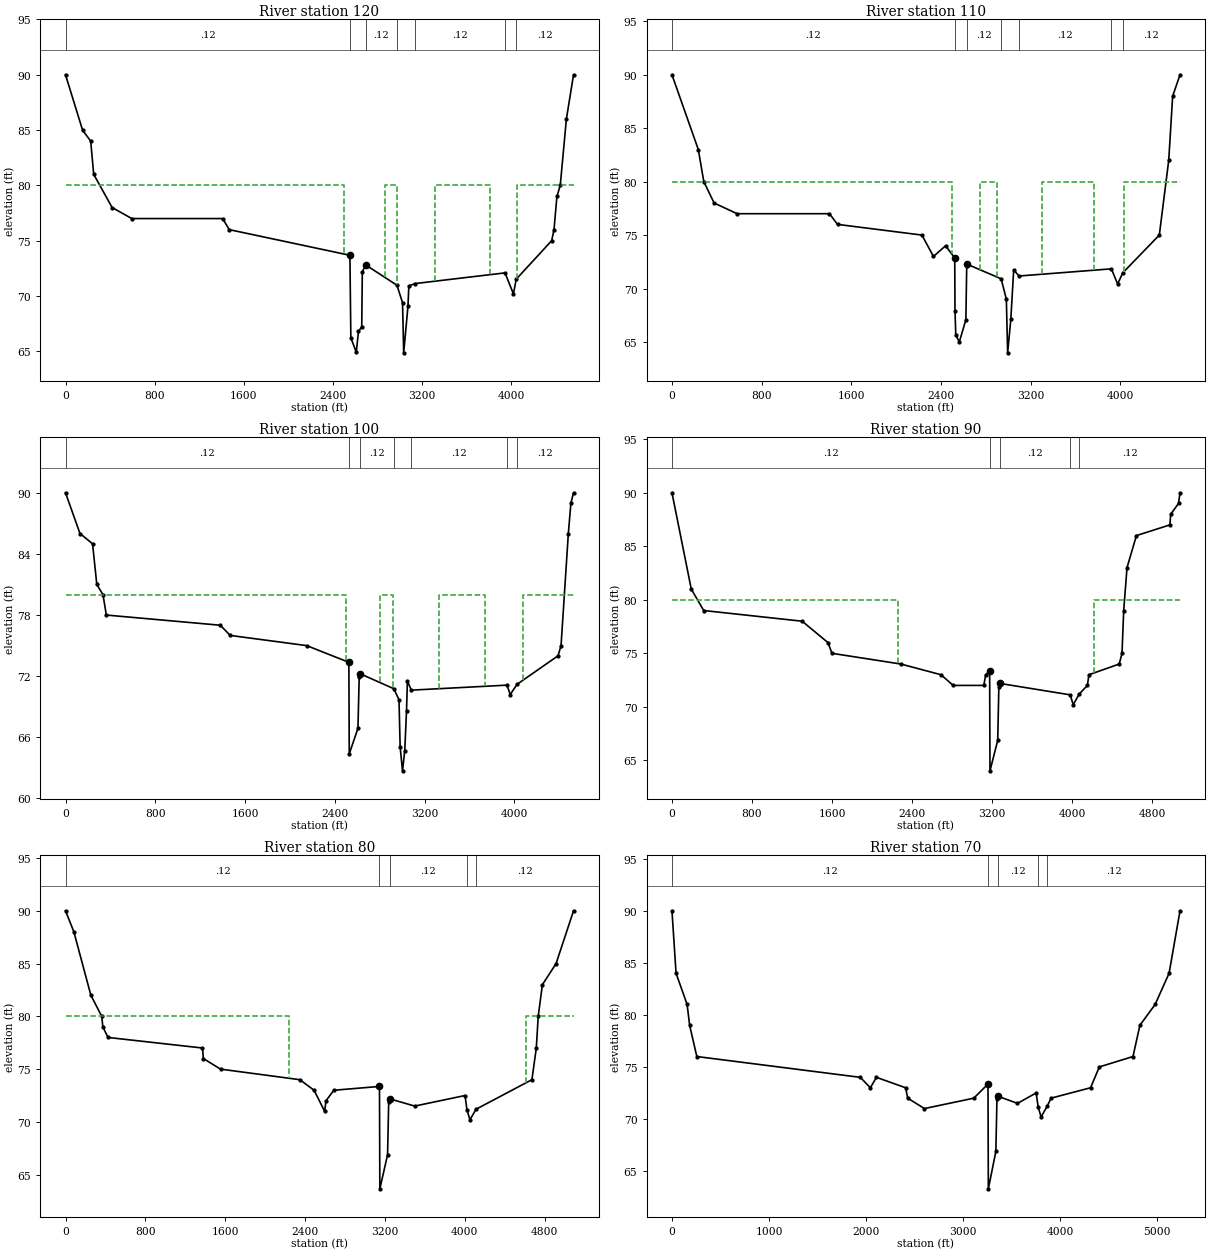
Type RM Length L Ch R = 1 ,120     ,52,40,22
BEGIN DESCRIPTION:
Stn 16+70
END DESCRIPTION:
#Sta/Elev= 30
       0      90     153      85     226      84     253      81     418      78
     595      77    1410      77    1469      76 2551.74   73.68 2560.11   66.22
 2608.77   64.92  2628.7   66.79 2657.91   67.21 2663.09   72.19 2693.21   72.81
 2973.99   70.97 3023.96   69.39 3034.21   64.86 3072.54   69.06  3080.4    70.9
 3133.99   71.12 3943.43   72.09 4018.76   70.19 4044.08   71.52    4362      75
    4383      76    4409      79    4439      80    4494      86 4558.25      90
#Mann= 7 ,-1 , 0
       0     .12       0 2551.74     .05       0 2693.21     .12       0
 2973.99     .05       0 3133.99     .12       0 3943.43     .05       0
 4044.08     .12       0
#XS Ineff= 4 ,-1
       0    2500      80    2864    2970      80    3319    3805      80
    4049 4558.25      80
Permanent Ineff=
       F       F       F       F
Bank Sta=2551.74,2693.21
XS Rating Curve= 0 ,0
Exp/Cntr=0.5,0.3

Type RM Length L Ch R = 1 ,110     ,45,40,80
BEGIN DESCRIPTION:
Stn 17+10
END DESCRIPTION:
#Sta/Elev= 30
       0      90     235      83     284      80     376      78     581      77
    1405      77    1477      76    2230      75    2333      73    2441      74
 2522.62   72.86  2525.2   67.88 2532.33   65.62 2564.01   65.01 2622.08   67.08
 2629.64   72.08 2635.86   72.26 2936.66   70.91 2983.21   69.01 2994.77   63.98
 3023.12   67.12 3048.67   71.74 3096.66   71.17  3920.3   71.84 3976.28   70.42
 4021.91   71.47    4348      75    4432      82    4467      88 4532.65      90
#Mann= 7 ,-1 , 0
       0     .12       0 2522.62     .05       0 2635.86     .12       0
 2936.66     .05       0 3096.66     .12       0  3920.3     .05       0
 4021.91     .12       0
#XS Ineff= 4 ,-1
       0    2498      80    2750    2900      80    3305    3767      80
    4033 4532.65      80
Permanent Ineff=
       F       F       F       F
Bank Sta=2522.62,2635.86
XS Rating Curve= 0 ,0
Exp/Cntr=0.5,0.3

Type RM Length L Ch R = 1 ,100     ,174,168.67,113.33
BEGIN DESCRIPTION:
Stn 17+50
END DESCRIPTION:
#Sta/Elev= 30
       0      90     129      86     241      85     279      81     334      80
     364      78    1380      77    1468      76    2150      75 2525.65   73.36
  2529.2   64.38 2606.63   66.88 2617.88    71.9 2628.16   72.23  2926.4   70.77
 2972.61   69.69  2982.8   65.06 3003.85   62.71 3023.82   64.67 3039.77   68.62
  3047.3   71.52 3082.57   70.63 3934.43   71.12 3964.38    70.2 4024.82    71.2
    4390      74    4417      75    4482      86    4505      89 4528.44      90
#Mann= 7 ,-1 , 0
       0     .12       0 2525.65     .05       0 2628.16     .12       0
  2926.4     .05       0 3082.57     .12       0 3934.43     .05       0
 4024.82     .12       0
#XS Ineff= 4 ,-1
       0    2504      80    2800    2920      80    3331    3741      80
    4078 4528.44      80
Permanent Ineff=
       F       F       F       F
Bank Sta=2525.65,2628.16
XS Rating Curve= 0 ,0
Exp/Cntr=0.5,0.3

Type RM Length L Ch R = 1 ,90      ,142.67,173.33,152.67
#Sta/Elev= 30
       0      90     193      81     317      79    1302      78    1560      76
    1600      75    2288      74    2690      73    2812      72    3118      72
    3137      73 3176.35   73.36  3179.9   64.02 3257.33   66.88 3268.58    71.9
 3276.96   72.19  3982.2   71.12 4012.15    70.2 4072.59    71.2    4154      72
    4169      73    4472      74    4500      75    4517      79    4550      83
    4644      86    4979      87    4987      88    5065      89    5080      90
#Mann= 5 ,-1 , 0
       0     .12       0 3176.35     .05       0 3276.96     .12       0
  3982.2     .05       0 4072.59     .12       0
#XS Ineff= 2 ,-1
       0    2264      80    4216    5080      80
Permanent Ineff=
       F       F
Bank Sta=3176.35,3276.96
XS Rating Curve= 0 ,0
Exp/Cntr=0.5,0.3

Type RM Length L Ch R = 1 ,80      ,123,151.5,98.5
#Sta/Elev= 30
       0      90      84      88     254      82     363      80     374      79
     426      78    1372      77    1381      76    1553      75    2347      74
    2490      73    2596      71    2609      72    2688      73 3145.05   73.36
  3148.6   63.66 3226.03   66.88 3237.28    71.9 3245.66   72.19    3498    71.5
    4002    72.5 4021.66   71.12 4051.61    70.2 4112.05    71.2    4672      74
    4716      77    4735      80    4777      83    4914      85    5089      90
#Mann= 5 ,-1 , 0
       0     .12       0 3145.05     .05       0 3245.66     .12       0
 4021.66     .05       0 4112.05     .12       0
#XS Ineff= 2 ,-1
       0    2235      80    4608    5089      80
Permanent Ineff=
       F       F
Bank Sta=3145.05,3245.66
XS Rating Curve= 0 ,0
Exp/Cntr=0.5,0.3

Type RM Length L Ch R = 1 ,70      ,,,
BEGIN DESCRIPTION:
Downstream
END DESCRIPTION:
#Sta/Elev= 30
       0      90      42      84     156      81     182      79     256      76
    1940      74    2044      73    2107      74    2407      73    2429      72
    2601      71    3110      72 3256.05   73.36  3259.6   63.29 3337.03   66.88
 3348.28    71.9 3356.66   72.19    3560    71.5    3752    72.5 3773.64   71.12
 3803.59    70.2 3864.03    71.2    3906      72    4313      73    4403      75
    4750      76    4821      79    4978      81    5122      84 5234.44      90
#Mann= 5 ,-1 , 0
       0     .12       0 3256.05     .05       0 3356.66     .12       0
 3773.64     .05       0 3864.03     .12       0
Bank Sta=3256.05,3356.66
XS Rating Curve= 0 ,0
Exp/Cntr=0.3,0.1
Stream Node=Little Pee Dee  ,S45             , 0 , 0 ,Upstream end
Stream Node=Little Pee Dee  ,S45             , 0 , 1 ,Downstream end
LCMann Table=0

--- S45MultipleBr.g03 (geometry) ---

Geom Title=Existing
Program Version=5.01

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
River Reach=Little Pee Dee  ,S45

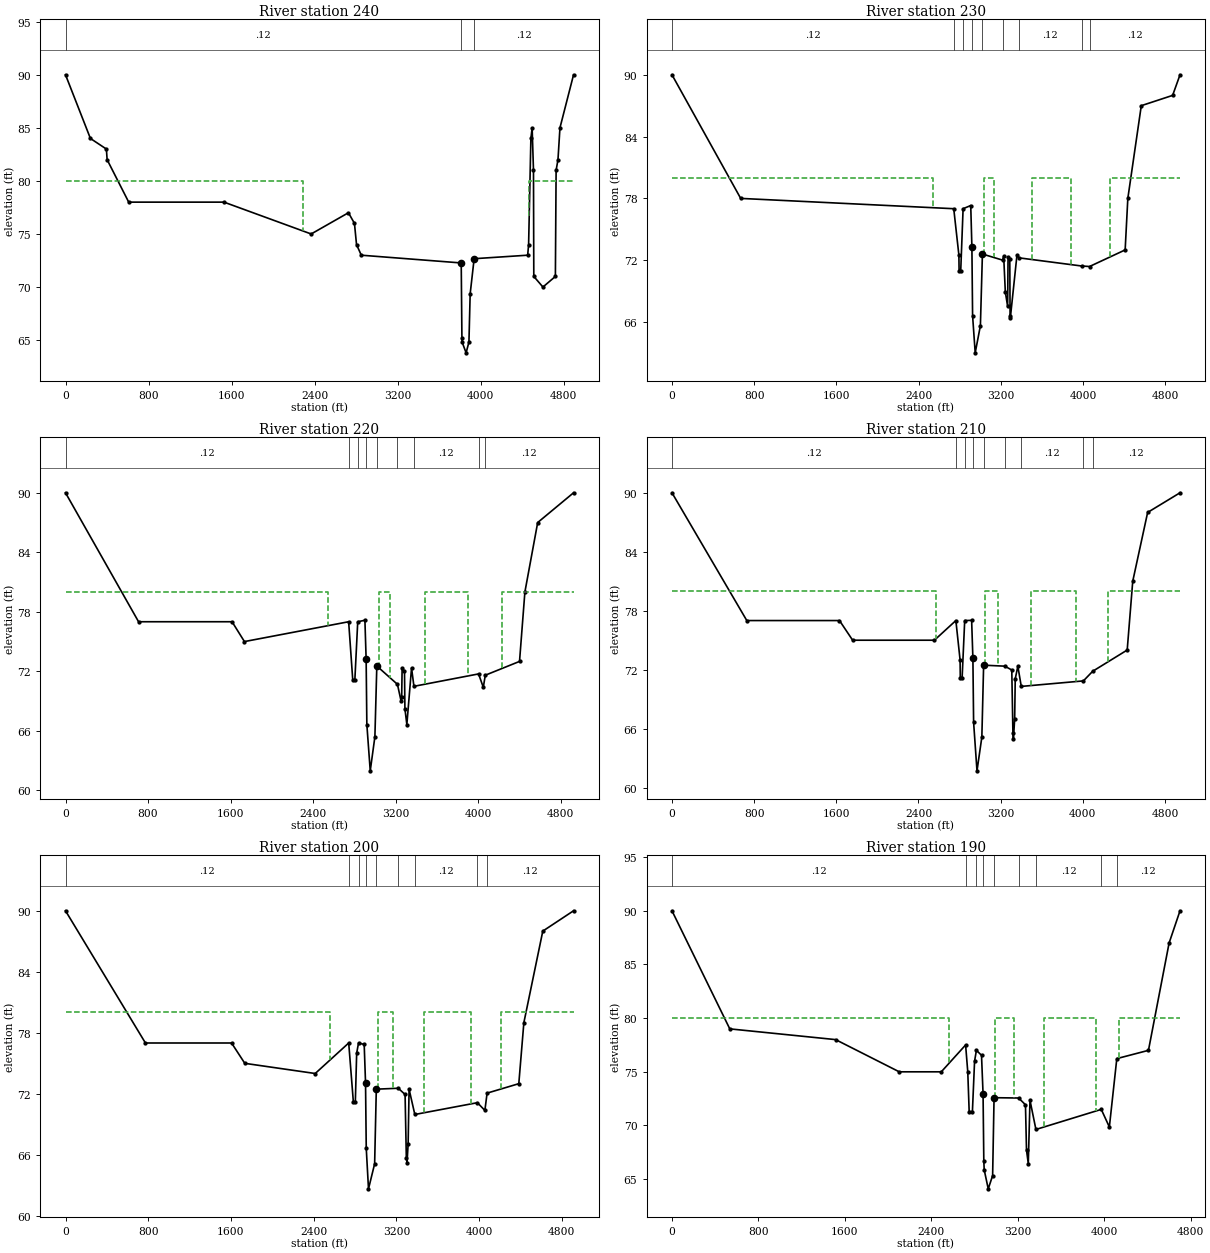
Type RM Length L Ch R = 1 ,240     ,18.67,179,27.89
#Sta/Elev= 30
       0      90     240      84     394      83     401      82     609      78
    1527      78    2367      75    2726      77    2784      76    2804      74
    2850      73 3812.72   72.27 3819.51   65.16 3820.95   64.82 3859.85    63.8
 3887.08   64.82 3898.94   69.36 3937.15   72.67    4453      73    4462      74
    4484      84    4496      85    4509      81    4512      71    4600      70
    4720      71    4727      81    4745      82    4764      85    4895      90
#Mann= 3 , 0 , 0
       0     .12       0 3812.72     .05       0 3937.15     .12       0
#XS Ineff= 2 ,-1
       0    2284      80    4468    4895      80
Permanent Ineff=
       F       F
Bank Sta=3812.72,3937.15
XS Rating Curve= 0 ,0
Exp/Cntr=0.5,0.3

Type RM Length L Ch R = 1 ,230     ,8,10,20
BEGIN DESCRIPTION:
Stn 12+90
END DESCRIPTION:
#Sta/Elev= 30
       0      90   668.8      78    2742      77    2792    72.5    2794      71
    2810      71    2833      77 2907.37   77.31 2918.64   73.26 2925.36   66.62
 2950.79   63.01 3001.36   65.65 3021.02    72.6 3217.03   72.01 3228.08   72.37
 3243.87   68.92 3266.36   67.52 3270.55    72.3 3287.33   72.11 3290.27   66.54
  3293.1   66.43 3357.36   72.51 3377.02   72.23 3985.41   71.44 4063.55   71.39
    4410      73    4436      78    4567      87    4872      88 4943.86      90
#Mann= 9 ,-1 , 0
       0     .12       0    2742     .05       0    2833     .12       0
 2918.64     .05       0 3021.02     .12       0 3217.03     .05       0
 3377.02     .12       0 3985.41     .05       0 4063.55     .12       0
#XS Ineff= 4 ,-1
       0    2540      80    3040    3129      80    3508    3880      80
    4260 4943.86      80
Permanent Ineff=
       F       F       F       F
Bank Sta=2918.64,3021.02
XS Rating Curve= 0 ,0
Exp/Cntr=0.5,0.3

Type RM Length L Ch R = 1 ,220     ,6,10,10
BEGIN DESCRIPTION:
Stn 13+00
END DESCRIPTION:
#Sta/Elev= 30
       0      90     708      77    1614      77    1734      75    2744      77
    2784    71.1    2804    71.1    2832      77 2901.64   77.15 2913.56    73.2
 2920.34   66.64 2953.23   61.97  2998.4   65.41 3016.98   72.54 3216.92   70.69
  3252.6   68.98 3257.85   69.37 3262.23    72.3 3285.22   72.02 3289.36   68.22
 3308.06   66.64 3353.49   72.34 3376.68   70.49 4003.07   71.74 4048.96   70.39
 4068.31   71.61    4400      73    4452      80    4576      87 4923.55      90
#Mann= 9 ,-1 , 0
       0     .12       0    2744     .05       0    2832     .12       0
 2913.56     .05       0 3016.98     .12       0 3216.92     .05       0
 3376.68     .12       0 4003.07     .05       0 4068.31     .12       0
#XS Ineff= 4 ,-1
       0    2548      80    3034    3144      80    3485    3898      80
    4234 4923.55      80
Permanent Ineff=
       F       F       F       F
Bank Sta=2913.56,3016.98
XS Rating Curve= 0 ,0
Exp/Cntr=0.5,0.3

Type RM Length L Ch R = 1 ,210     ,8,10,10
BEGIN DESCRIPTION:
Stn 13+10
END DESCRIPTION:
#Sta/Elev= 30
       0      90   728.5      77    1631      77    1759      75    2555      75
    2764      77    2805      73    2807    71.2    2825    71.2    2850      77
 2917.46   77.02 2929.82   73.14 2936.64   66.65 2969.59   61.71 3016.91   65.14
 3034.24   72.46 3240.69   72.36 3308.33   71.97 3319.38   65.58 3324.41   64.95
 3336.43      67 3342.03   71.07 3367.41   72.36 3400.68    70.3 4005.49   70.86
 4095.98   71.84    4432      74    4486      81    4631      88 4946.23      90
#Mann= 9 ,-1 , 0
       0     .12       0    2764     .05       0    2850     .12       0
 2929.82     .05       0 3034.24     .12       0 3240.69     .05       0
 3400.68     .12       0 4005.49     .05       0 4095.98     .12       0
#XS Ineff= 4 ,-1
       0    2573      80    3048    3178      80    3498    3931      80
    4247 4946.23      80
Permanent Ineff=
       F       F       F       F
Bank Sta=2929.82,3034.24
XS Rating Curve= 0 ,0
Exp/Cntr=0.5,0.3

Type RM Length L Ch R = 1 ,200     ,15,20,50
BEGIN DESCRIPTION:
Stn 13+20
END DESCRIPTION:
#Sta/Elev= 30
       0      90     773      77    1606      77    1734      75    2415      74
    2739      77    2784    71.2    2803    71.2    2816      76    2834      77
 2888.71   76.86 2901.71   73.08 2908.59   66.66 2930.34   62.66 2989.71   65.12
  3005.9   72.46 3218.38   72.55 3284.13   71.94 3296.25   65.73 3302.91   65.22
 3313.75   67.09 3322.86   72.46 3378.38   69.97 3983.49   71.13 4055.94   70.37
 4077.34   72.07    4384      73    4433      79    4616      88 4913.48      90
#Mann= 9 ,-1 , 0
       0     .12       0    2739     .05       0    2834     .12       0
 2901.71     .05       0  3005.9     .12       0 3218.38     .05       0
 3378.38     .12       0 3983.49     .05       0 4077.34     .12       0
#XS Ineff= 4 ,-1
       0    2558      80    3019    3165      80    3464    3918      80
    4213 4913.48      80
Permanent Ineff=
       F       F       F       F
Bank Sta=2901.71,3005.9
XS Rating Curve= 0 ,0
Exp/Cntr=0.5,0.3

Type RM Length L Ch R = 1 ,190     ,8,10,10
BEGIN DESCRIPTION:
Stn 13+40
END DESCRIPTION:
#Sta/Elev= 30
       0      90     535      79    1514      78    2103      75    2492      75
    2717    77.5    2737      75    2750    71.3    2780    71.3    2800      76
    2817      77  2864.2   76.54 2878.48   72.95 2885.48   66.69 2889.15   65.87
 2926.42    64.1 2967.08   65.33 2980.28   72.59  3207.6   72.56  3270.9   71.93
 3280.47   67.71 3296.98   66.45 3312.77   72.35  3367.6   69.63 3972.36    71.5
 4047.17   69.86 4116.08   76.23    4409      77    4600      87 4700.93      90
#Mann= 9 ,-1 , 0
       0     .12       0    2717     .05       0    2817     .12       0
 2878.48     .05       0 2980.28     .12       0  3207.6     .05       0
  3367.6     .12       0 3972.36     .05       0 4116.08     .12       0
#XS Ineff= 4 ,-1
       0    2560      80    2993    3166      80    3440    3919      80
    4139 4700.93      80
Permanent Ineff=
       F       F       F       F
Bank Sta=2878.48,2980.28
XS Rating Curve= 0 ,0
Exp/Cntr=0.5,0.3

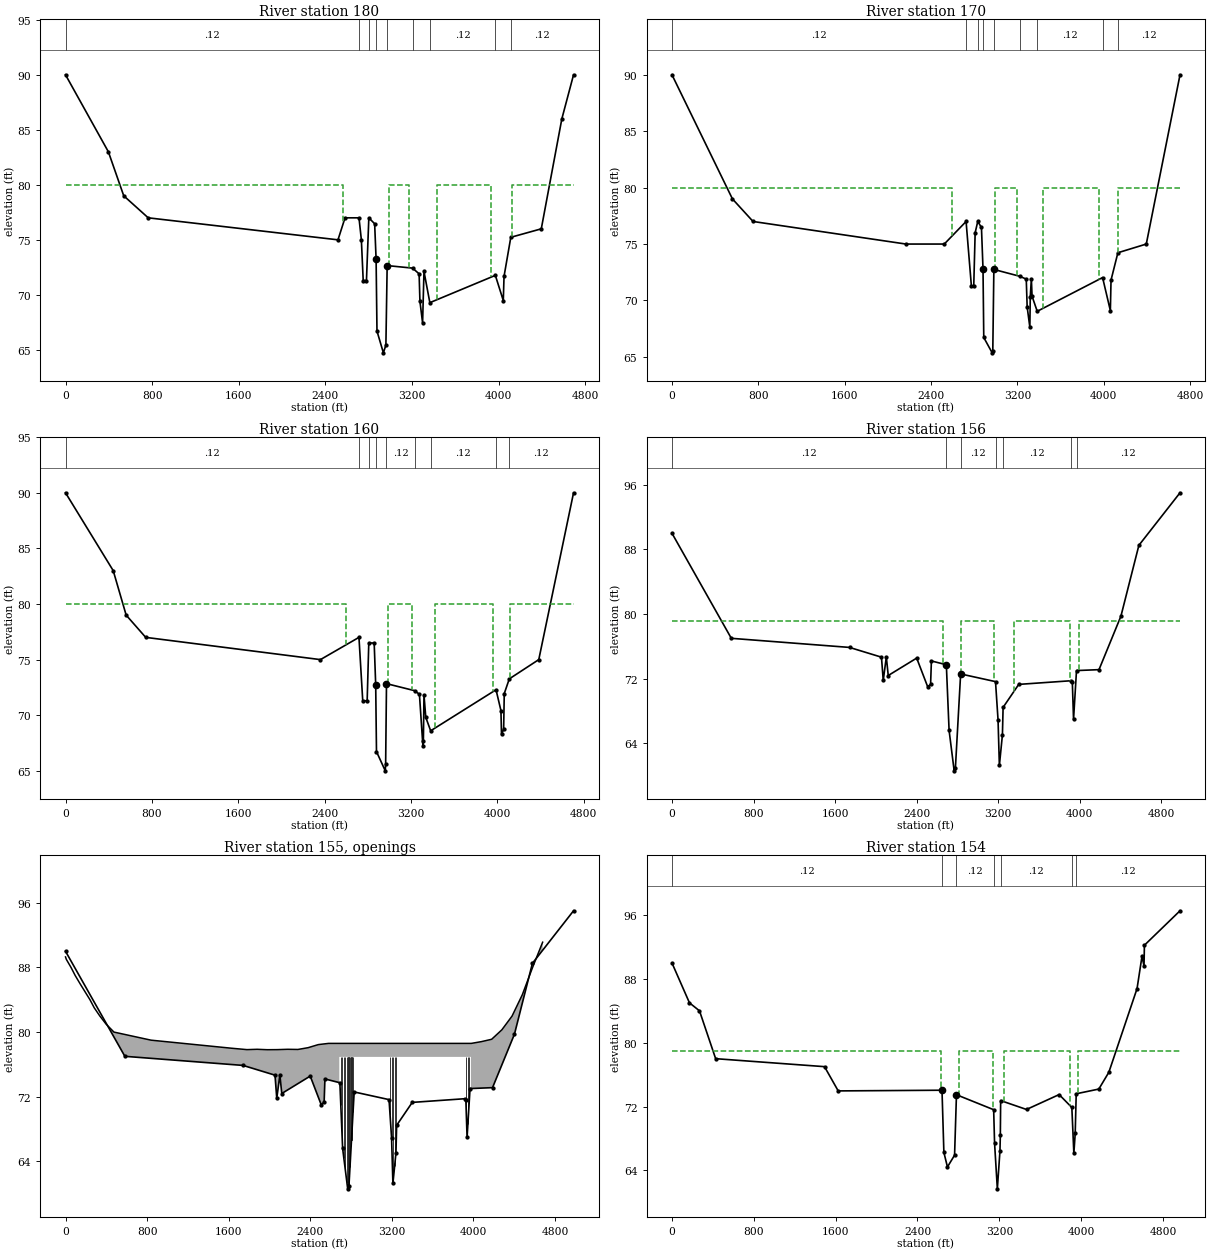
Type RM Length L Ch R = 1 ,180     ,9,10,10
BEGIN DESCRIPTION:
Stn 13+50
END DESCRIPTION:
#Sta/Elev= 30
       0      90     396      83     538      79     764      77    2517      75
    2582      77    2711      77    2733      75    2750    71.3    2780    71.3
    2802      77 2855.69   76.46 2869.15   73.23 2877.21   66.71 2936.37   64.73
 2959.62   65.44 2971.31   72.66 3205.61   72.43 3266.47   71.91 3273.94   69.42
 3298.54   67.45  3311.4   72.13 3365.61   69.29 3970.69   71.77 4044.06   69.48
  4050.8   71.67 4113.38   75.23    4395      76    4585      86 4693.01      90
#Mann= 9 ,-1 , 0
       0     .12       0    2711     .05       0    2802     .12       0
 2869.15     .05       0 2971.31     .12       0 3205.61     .05       0
 3365.61     .12       0 3970.69     .05       0 4113.38     .12       0
#XS Ineff= 4 ,-1
       0    2566      80    2984    3173      80    3428    3927      80
    4125 4693.01      80
Permanent Ineff=
       F       F       F       F
Bank Sta=2869.15,2971.31
XS Rating Curve= 0 ,0
Exp/Cntr=0.5,0.3

Type RM Length L Ch R = 1 ,170     ,10,10,10
BEGIN DESCRIPTION:
Stn 13+60
END DESCRIPTION:
#Sta/Elev= 30
       0      90     560      79     751      77    2167      75    2522      75
    2724      77    2773    71.3    2795    71.3    2808      76    2832      77
 2866.34   76.47 2880.74   72.81 2887.76   66.72 2965.58   65.36 2971.42   65.54
 2981.26   72.75  3222.9   72.14 3281.31   71.89 3289.71   69.43  3314.6   67.63
 3318.49   70.33 3328.69   71.93 3335.07   70.38  3382.9   69.04  3988.3   72.03
 4060.25    69.1 4066.53   71.81 4129.98   74.23    4393      75 4705.39      90
#Mann= 9 ,-1 , 0
       0     .12       0    2724     .05       0    2832     .12       0
 2880.74     .05       0 2981.26     .12       0  3222.9     .05       0
  3382.9     .12       0  3988.3     .05       0 4129.98     .12       0
#XS Ineff= 4 ,-1
       0    2592      80    2994    3200      80    3433    3953      80
    4131 4705.39      80
Permanent Ineff=
       F       F       F       F
Bank Sta=2880.74,2981.26
XS Rating Curve= 0 ,0
Exp/Cntr=0.5,0.3

Type RM Length L Ch R = 1 ,160     ,129.99,110.01,24.99
BEGIN DESCRIPTION:
Stn 13+70
END DESCRIPTION:
#Sta/Elev= 30
       0      90     442      83     562      79     743      77    2362      75
    2719      77    2754    71.3    2795    71.3    2810    76.5    2860   76.49
 2874.04   72.74 2881.32   66.73 2962.82      65 2966.23   65.64 2974.12   72.84
 3233.83   72.21  3279.2   71.88 3311.71    67.2 3315.76   67.66  3321.4   71.82
 3338.06   69.81 3383.23    68.6 3988.94   72.29 4034.42   70.42 4039.66    68.3
 4059.44   68.72 4065.28   71.95 4112.02   73.27    4385      75  4707.2      90
#Mann= 9 ,-1 , 0
       0     .12       0    2719     .05       0    2810     .12       0
 2874.04     .05       0 2974.12     .12       0 3233.83     .05       0
 3383.23     .12       0 3988.94     .05       0 4112.02     .12       0
#XS Ineff= 4 ,-1
       0    2601      80    2988    3210      80    3422    3963      80
    4123  4707.2      80
Permanent Ineff=
       F       F       F       F
Bank Sta=2874.04,2974.12
XS Rating Curve= 0 ,0
Exp/Cntr=0.5,0.3

Type RM Length L Ch R = 1 ,156     ,60,60,60
BEGIN DESCRIPTION:
Bridge - Upstream
END DESCRIPTION:
#Sta/Elev= 30
       0      90     582      77 1741.06 75.8743 2054.45 74.6666 2071.79 71.7957
 2102.06 74.6859 2120.88 72.3984 2399.79 74.5524 2507.24 71.0181 2536.19 71.3033
 2544.06    74.2 2690.58   73.73 2717.54 65.6107 2767.44 60.6025 2779.51 60.9536
 2830.78 72.5917 3172.78 71.6429 3197.71 66.8991 3210.64 61.2638 3240.62 65.0586
 3247.21 68.4574 3400.53    71.3 3913.63 71.7514 3926.05 71.6037 3938.04  66.967
 3967.04 73.0092 4187.68 73.1239 4402.62 79.7382 4578.71 88.5063 4982.15 95.0095
#Mann= 7 ,-1 , 0
       0     .12       0 2690.58     .05       0 2830.78     .12       0
 3172.78     .05       0 3247.21     .12       0 3913.63     .05       0
 3967.04     .12       0
#XS Ineff= 4 ,-1
       0    2660    79.1    2839    3154    79.1    3350    3905    79.1
    3994 4982.15    79.1
Permanent Ineff=
       F       F       F       F
Bank Sta=2690.58,2830.78
XS Rating Curve= 0 ,0
Exp/Cntr=0.5,0.3

Type RM Length L Ch R = 4 ,155     ,,,
Bridge Culvert--1,0,-1,-1, 0
Deck Dist Width WeirC Skew NumUp NumDn MinLoCord MaxHiCord MaxSubmerge Is_Ogee
15,30,2.6,0, 55, 50, , , 0.98, 0, 0,0,,
       0       8      54      95     142     191     240     282     336     397
     475     839    1630    1779    1879    1979    2079    2179    2279    2379
    2479    2579  2684.8  2684.8  2834.8  2834.8    2879    2979    3079  3167.8
  3167.8  3167.8  3257.8  3257.8    3279    3329    3379    3429    3479    3579
    3679    3779    3879  3915.8  3915.8  3975.8  3975.8    3979    4079    4179
    4279    4379    4479    4579    4679
    89.3      89      88      87      86      85      84      83      82      81
      80      79      78   77.83   77.87   77.82   77.83   77.87   77.85   78.07
   78.45    78.6    78.6    78.6    78.6    78.6    78.6    78.6    78.6    78.6
    78.6    78.6    78.6    78.6    78.6    78.6    78.6    78.6    78.6    78.6
    78.6    78.6    78.6    78.6    78.6    78.6    78.6    78.6   78.82   79.11
   80.28   81.98    84.6   87.95   91.12
                                                                                
                                                                                
                           76.93   76.93
           76.93   76.93
                                   76.93   76.93
                                        
     240     282     336     397     475     839    1630    1779    1879    1979
    2079    2179    2279    2379    2479    2579  2635.3  2635.3  2785.3  2785.3
    2879    2979    3079  3142.8  3142.8  3232.8  3232.8    3279    3329    3379
    3429    3479    3579    3679    3779    3879  3899.9  3899.9  3959.9  3959.9
    3979    4079    4179    4279    4379    4479    4579    4679    4779    4879
      84      83      82      81      80      79      78   77.83   77.87   77.82
   77.83   77.87   77.85   78.07   78.45    78.6    78.6    78.6    78.6    78.6
    78.6    78.6    78.6    78.6    78.6    78.6    78.6    78.6    78.6    78.6
    78.6    78.6    78.6    78.6    78.6    78.6    78.6    78.6    78.6    78.6
    78.6   78.82   79.11   80.28   81.98    84.6   87.95   91.12   95.31   95.08
                                                                                
                                                           76.93   76.93
                                   76.93   76.93
                                                           76.93   76.93
                                                                                
Pier Skew, UpSta & Num, DnSta & Num=  ,2699.8, 2 ,2650.3, 2 , 0 , 0 , 0 ,,
    1.17    1.17
      60    78.6
    1.17    1.17
      60    78.6
Pier Skew, UpSta & Num, DnSta & Num=  ,2714.8, 2 ,2665.3, 2 , 0 , 0 , 0 ,,
    1.17    1.17
      60    78.6
    1.17    1.17
      60    78.6
Pier Skew, UpSta & Num, DnSta & Num=  ,2729.8, 2 ,2680.3, 2 , 0 , 0 , 0 ,,
    1.17    1.17
      60    78.6
    1.17    1.17
      60    78.6
Pier Skew, UpSta & Num, DnSta & Num=  ,2744.8, 2 ,2695.3, 2 , 0 , 0 , 0 ,,
    1.17    1.17
      60    78.6
    1.17    1.17
      60    78.6
Pier Skew, UpSta & Num, DnSta & Num=  ,2759.8, 2 ,2710.3, 2 , 0 , 0 , 0 ,,
    1.17    1.17
      60    78.6
    1.17    1.17
      60    78.6
Pier Skew, UpSta & Num, DnSta & Num=  ,2774.8, 2 ,2725.3, 2 , 0 , 0 , 0 ,,
    1.17    1.17
      60    78.6
    1.17    1.17
      60    78.6
Pier Skew, UpSta & Num, DnSta & Num=  ,2789.8, 2 ,2740.3, 2 , 0 , 0 , 0 ,,
    1.17    1.17
      60    78.6
    1.17    1.17
      60    78.6
Pier Skew, UpSta & Num, DnSta & Num=  ,2804.8, 2 ,2755.3, 2 , 0 , 0 , 0 ,,
    1.17    1.17
      60    78.6
    1.17    1.17
      60    78.6
Pier Skew, UpSta & Num, DnSta & Num=  ,2819.8, 2 ,2770.3, 2 , 0 , 0 , 0 ,,
    1.17    1.17
      60    78.6
    1.17    1.17
      60    78.6
Pier Skew, UpSta & Num, DnSta & Num=  ,3182.8, 2 ,3157.8, 2 , 0 , 0 , 0 ,,
    1.17    1.17
      60    78.6
    1.17    1.17
      60    78.6
Pier Skew, UpSta & Num, DnSta & Num=  ,3197.8, 2 ,3172.8, 2 , 0 , 0 , 0 ,,
    1.17    1.17
      60    78.6
    1.17    1.17
      60    78.6
Pier Skew, UpSta & Num, DnSta & Num=  ,3212.8, 2 ,3187.8, 2 , 0 , 0 , 0 ,,
    1.17    1.17
      60    78.6
    1.17    1.17
      60    78.6
Pier Skew, UpSta & Num, DnSta & Num=  ,3227.8, 2 ,3202.8, 2 , 0 , 0 , 0 ,,
    1.17    1.17
      60    78.6
    1.17    1.17
      60    78.6
Pier Skew, UpSta & Num, DnSta & Num=  ,3242.8, 2 ,3217.8, 2 , 0 , 0 , 0 ,,
    1.17    1.17
      60    78.6
    1.17    1.17
      60    78.6
Pier Skew, UpSta & Num, DnSta & Num=  ,3930.8, 2 ,3914.9, 2 , 0 , 0 , 0 ,,
    1.17    1.17
      60    78.6
    1.17    1.17
      60    78.6
Pier Skew, UpSta & Num, DnSta & Num=  ,3945.8, 2 ,3929.9, 2 , 0 , 0 , 0 ,,
    1.17    1.17
      60    78.6
    1.17    1.17
      60    78.6
Pier Skew, UpSta & Num, DnSta & Num=  ,3960.8, 2 ,3944.8, 2 , 0 , 0 , 0 ,,
    1.17    1.17
      60    78.6
    1.17    1.17
      60    78.6
Abutment Skew #Up #Dn= , 2 , 2
  2684.8  2686.8
   76.93      60
  2635.3  2637.3
   76.93      60
Abutment Skew #Up #Dn= , 2 , 2
  2832.8  2834.8
      60   76.93
  2783.3  2785.3
      60   76.93
Abutment Skew #Up #Dn= , 2 , 2
  3167.8  3169.8
   76.93      60
  3142.8  3144.8
   76.93      60
Abutment Skew #Up #Dn= , 2 , 2
  3255.8  3257.8
      60   76.93
  3230.8  3232.8
      60   76.93
Abutment Skew #Up #Dn= , 2 , 2
  3915.8  3917.8
   76.93      60
  3899.9  3901.9
   76.93      60
Abutment Skew #Up #Dn= , 2 , 2
  3973.8  3975.8
      60   76.93
  3957.9  3959.9
      60   76.93
BR Coef=-1 , 0 , 0 ,, 0 ,,,0.8,-1,,0,
WSPro=,,,, 1 ,,,, 0 ,,,, 0 ,,,,-1 ,-1 ,-1 , 0 , 0 , 0 , 0 , 0
BC Mult= 3 ,0,3095,0,3045.5
BC Mult= 3 ,2900,3700,2850.5,3650.5
BC Mult= 3 ,3400,4982.15,3350.5,4966.11
BC Design=,, 0 ,, 0 ,,,,,,
BC Use User HTab Curves=0
BC User HTab FreeFlow(D)= 0

Type RM Length L Ch R = 1 ,154     ,5,70,35
BEGIN DESCRIPTION:
Bridge - Downstream
END DESCRIPTION:
#Sta/Elev= 30
       0      90     171      85     269      84     427      78    1491      77
 1624.95 73.9596 2639.55 74.0448 2657.88 66.2491 2692.74 64.4206 2762.43 65.9018
 2780.89 73.4811 3144.53 71.6023 3153.45 67.3865 3180.54   61.68 3206.25 66.4675
 3209.74 68.3821 3212.84 72.7469 3465.52 71.6316 3784.49    73.5 3908.73  71.881
 3928.43 66.1158  3941.6 68.6294 3951.49    73.6  4172.4 74.1905 4270.42 76.2945
 4546.17 86.7895 4594.39 90.8314 4614.24 89.6382 4618.07 92.2247 4966.11 96.5451
#Mann= 7 ,-1 , 0
       0     .12       0 2639.55     .05       0 2780.89     .12       0
 3144.53     .05       0 3212.84     .12       0 3908.73     .05       0
 3951.49     .12       0
#XS Ineff= 4 ,-1
       0    2633      79    2807    3135      79    3241    3890      79
    3965 4966.11      79
Permanent Ineff=
       F       F       F       F
Bank Sta=2639.55,2780.89
XS Rating Curve= 0 ,0
Exp/Cntr=0.5,0.3