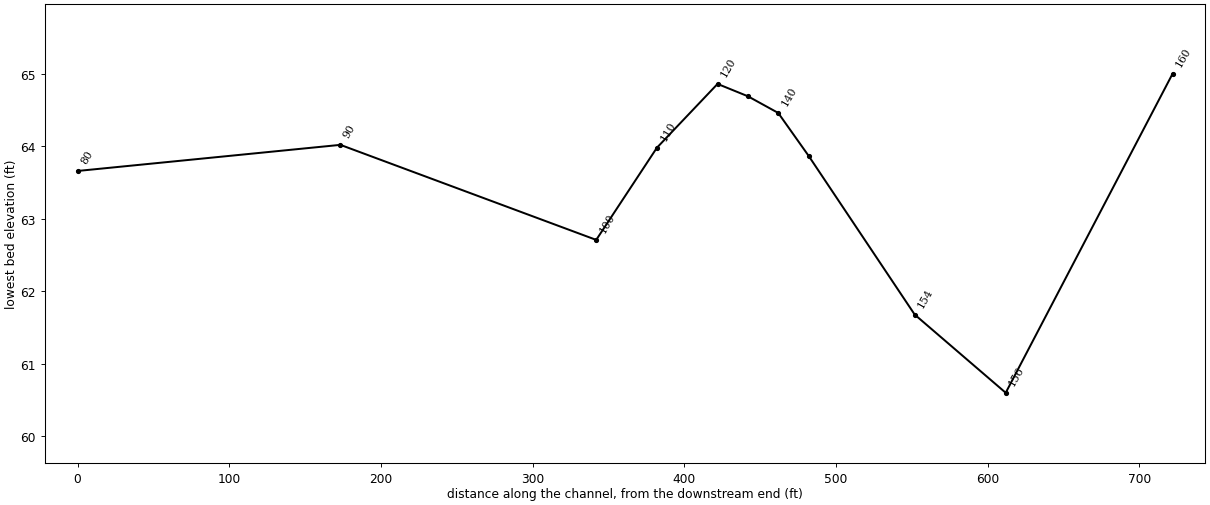
HEC-RAS study S45MultipleBr.prj: S45 Multiple Br

--- S45MultipleBr.g07 (geometry) --- (continued)

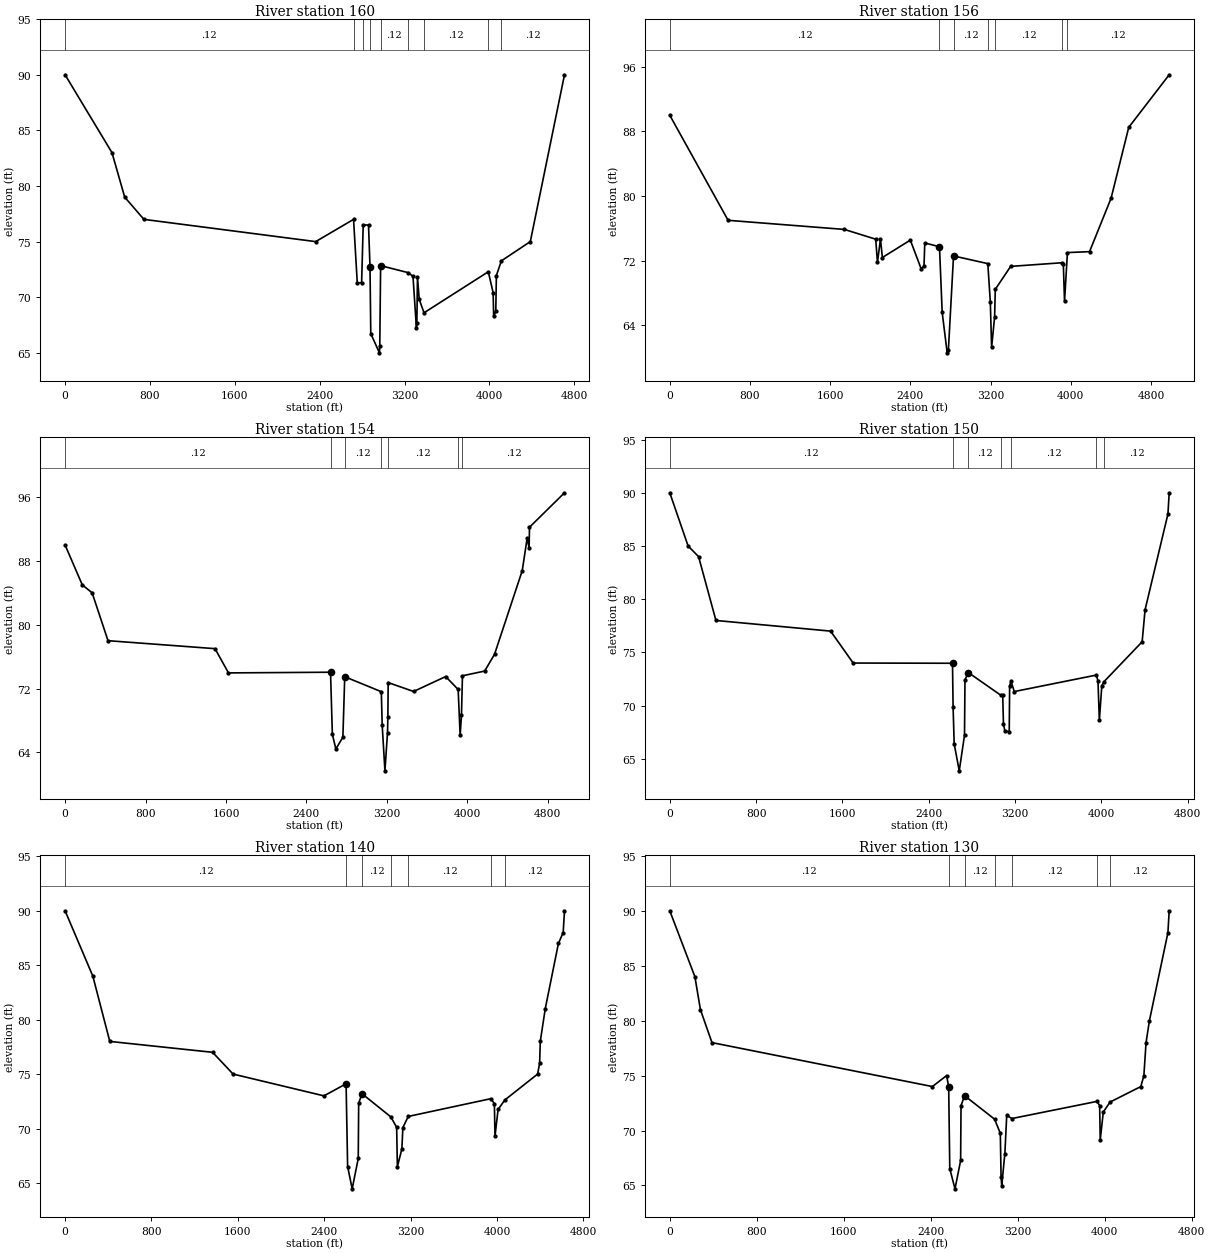
Type RM Length L Ch R = 1 ,160     ,129.99,110.01,24.99
BEGIN DESCRIPTION:
Stn 13+70
END DESCRIPTION:
#Sta/Elev= 30
       0      90     442      83     562      79     743      77    2362      75
    2719      77    2754    71.3    2795    71.3    2810    76.5    2860   76.49
 2874.04   72.74 2881.32   66.73 2962.82      65 2966.23   65.64 2974.12   72.84
 3233.83   72.21  3279.2   71.88 3311.71    67.2 3315.76   67.66  3321.4   71.82
 3338.06   69.81 3383.23    68.6 3988.94   72.29 4034.42   70.42 4039.66    68.3
 4059.44   68.72 4065.28   71.95 4112.02   73.27    4385      75  4707.2      90
#Mann= 9 ,-1 , 0
       0     .12       0    2719     .05       0    2810     .12       0
 2874.04     .05       0 2974.12     .12       0 3233.83     .05       0
 3383.23     .12       0 3988.94     .05       0 4112.02     .12       0
#XS Ineff= 2 , 0
Permanent Ineff=
       F       F
Bank Sta=2874.04,2974.12
XS Rating Curve= 0 ,0
Exp/Cntr=0.5,0.3

Type RM Length L Ch R = 1 ,156     ,60,60,60
BEGIN DESCRIPTION:
Bridge - Upstream
END DESCRIPTION:
#Sta/Elev= 30
       0      90     582      77 1741.06 75.8743 2054.45 74.6666 2071.79 71.7957
 2102.06 74.6859 2120.88 72.3984 2399.79 74.5524 2507.24 71.0181 2536.19 71.3033
 2544.06    74.2 2690.58   73.73 2717.54 65.6107 2767.44 60.6025 2779.51 60.9536
 2830.78 72.5917 3172.78 71.6429 3197.71 66.8991 3210.64 61.2638 3240.62 65.0586
 3247.21 68.4574 3400.53    71.3 3913.63 71.7514 3926.05 71.6037 3938.04  66.967
 3967.04 73.0092 4187.68 73.1239 4402.62 79.7382 4578.71 88.5063 4982.15 95.0095
#Mann= 7 ,-1 , 0
       0     .12       0 2690.58     .05       0 2830.78     .12       0
 3172.78     .05       0 3247.21     .12       0 3913.63     .05       0
 3967.04     .12       0
#XS Ineff= 2 , 0
Permanent Ineff=
       F       F
Bank Sta=2690.58,2830.78
XS Rating Curve= 0 ,0
Exp/Cntr=0.5,0.3

Type RM Length L Ch R = 1 ,154     ,5,70,35
BEGIN DESCRIPTION:
Bridge - Downstream
END DESCRIPTION:
#Sta/Elev= 30
       0      90     171      85     269      84     427      78    1491      77
 1624.95 73.9596 2639.55 74.0448 2657.88 66.2491 2692.74 64.4206 2762.43 65.9018
 2780.89 73.4811 3144.53 71.6023 3153.45 67.3865 3180.54   61.68 3206.25 66.4675
 3209.74 68.3821 3212.84 72.7469 3465.52 71.6316 3784.49    73.5 3908.73  71.881
 3928.43 66.1158  3941.6 68.6294 3951.49    73.6  4172.4 74.1905 4270.42 76.2945
 4546.17 86.7895 4594.39 90.8314 4614.24 89.6382 4618.07 92.2247 4966.11 96.5451
#Mann= 7 ,-1 , 0
       0     .12       0 2639.55     .05       0 2780.89     .12       0
 3144.53     .05       0 3212.84     .12       0 3908.73     .05       0
 3951.49     .12       0
#XS Ineff= 2 , 0
Permanent Ineff=
       F       F
Bank Sta=2639.55,2780.89
XS Rating Curve= 0 ,0
Exp/Cntr=0.5,0.3

Type RM Length L Ch R = 1 ,150     ,16,20,18
BEGIN DESCRIPTION:
Stn 16+10
END DESCRIPTION:
#Sta/Elev= 30
       0      90     170      85     267      84     428      78    1491      77
    1700      74 2620.97   73.98 2626.37    69.9 2636.56   66.41 2683.42   63.87
 2732.31   67.22 2736.61   72.41    2767   73.11 3072.25   70.95  3086.5   70.96
 3093.21   68.29 3105.88   67.63 3146.86   67.54 3150.57   71.84  3162.9   72.31
  3193.6   71.32 3954.19   72.87 3969.57   72.32 3982.25   68.61 4005.13   71.88
 4026.35   72.26    4379      76    4406      79    4618      88 4629.68      90
#Mann= 7 ,-1 , 0
       0     .12       0 2620.97     .05       0    2767     .12       0
 3072.25     .05       0  3162.9     .12       0 3954.19     .05       0
 4026.35     .12       0
#XS Ineff= 2 , 0
Permanent Ineff=
       F       F
Bank Sta=2620.97,2767
XS Rating Curve= 0 ,0
Exp/Cntr=0.5,0.3

Type RM Length L Ch R = 1 ,140     ,18,20,10
BEGIN DESCRIPTION:
Stn 16+30
END DESCRIPTION:
#Sta/Elev= 30
       0      90     257      84     414      78    1366      77    1556      75
    2397      73 2601.95   74.11 2616.15   66.51  2658.4   64.46 2714.57   67.25
 2718.53   72.34    2750   73.19 3017.26   71.06 3070.21    70.1 3076.84   66.49
 3118.23   68.12 3127.89   70.09 3177.27   71.11 3942.06   72.74 3974.94   72.29
 3980.73   69.28 4009.21   71.75 4071.69   72.62    4375      75    4394      76
    4400      78    4446      81    4568      87    4612      88 4624.22      90
#Mann= 7 ,-1 , 0
       0     .12       0 2601.95     .05       0    2750     .12       0
 3017.26     .05       0 3177.27     .12       0 3942.06     .05       0
 4071.69     .12       0
#XS Ineff= 2 , 0
Permanent Ineff=
       F       F
Bank Sta=2601.95,2750
XS Rating Curve= 0 ,0
Exp/Cntr=0.5,0.3

Type RM Length L Ch R = 1 ,130     ,17,20,114
BEGIN DESCRIPTION:
Stn 16+50
END DESCRIPTION:
#Sta/Elev= 30
       0      90     231      84     282      81     388      78    2415      74
    2546      75 2564.87   73.98    2575   66.53 2622.98   64.69 2674.83   67.27
 2678.45   72.27    2711   73.17 2987.02   71.03 3039.68   69.75 3046.77   65.76
 3052.75   64.97 3081.61    67.9 3098.65   71.37 3147.03   71.09 3928.83   72.65
 3953.31   72.27 3958.57   69.15 3986.92   71.68 4049.33   72.59    4332      74
    4360      75    4380      78    4411      80    4581      88 4592.77      90
#Mann= 7 ,-1 , 0
       0     .12       0 2564.87     .05       0    2711     .12       0
 2987.02     .05       0 3147.03     .12       0 3928.83     .05       0
 4049.33     .12       0
#XS Ineff= 2 , 0
Permanent Ineff=
       F       F
Bank Sta=2564.87,2711
XS Rating Curve= 0 ,0
Exp/Cntr=0.5,0.3

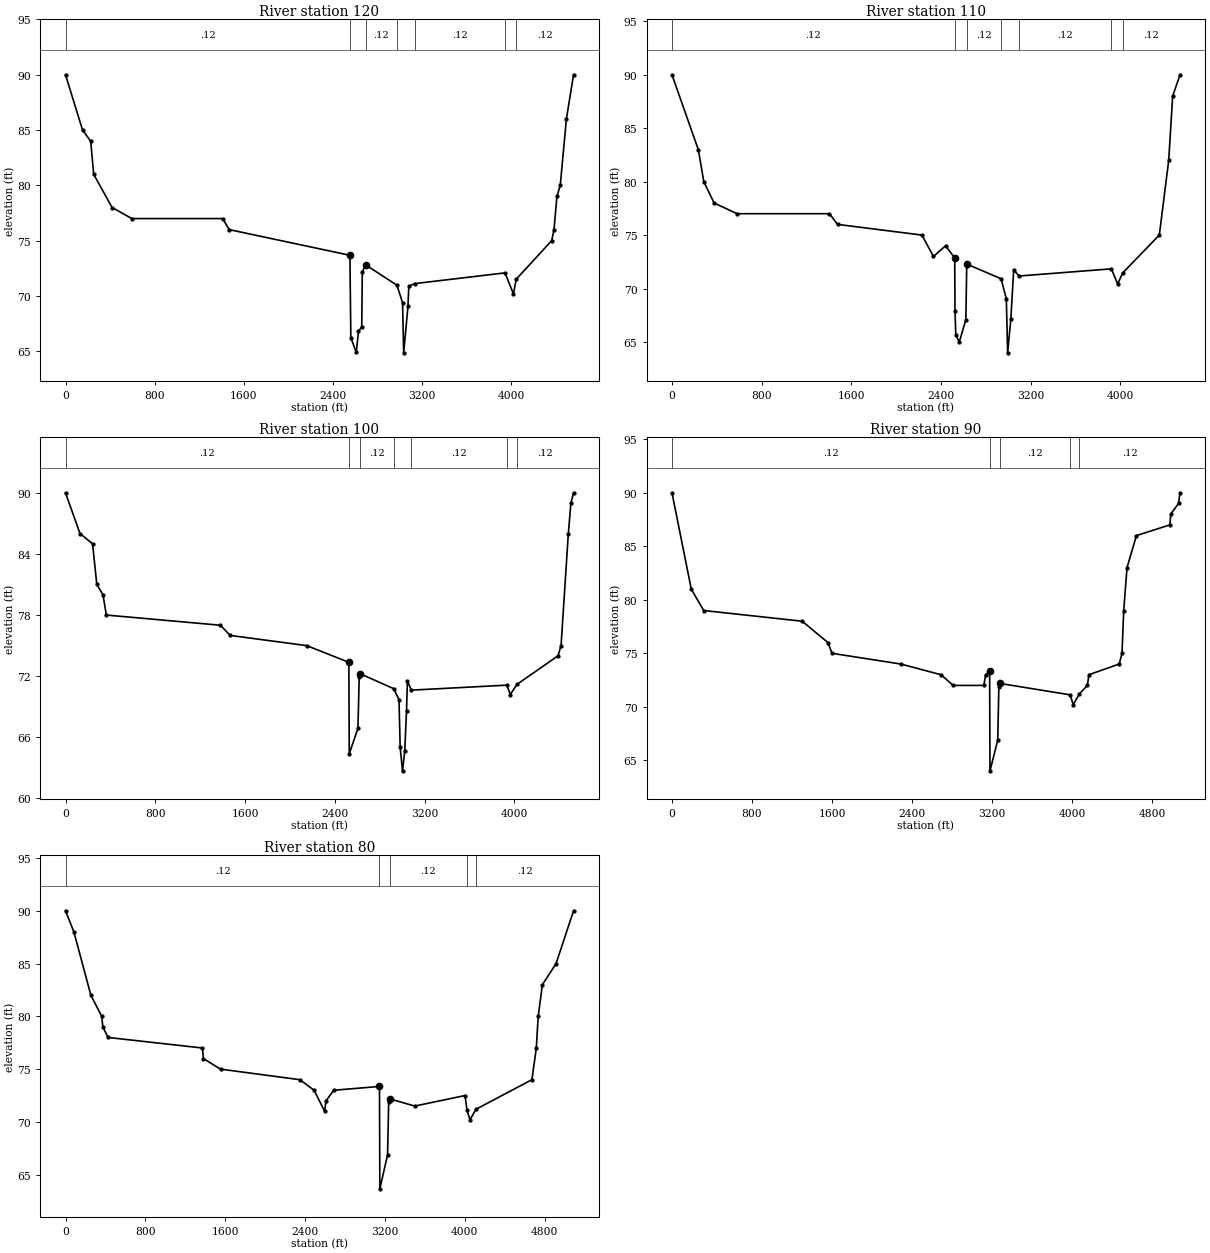
Type RM Length L Ch R = 1 ,120     ,52,40,22
BEGIN DESCRIPTION:
Stn 16+70
END DESCRIPTION:
#Sta/Elev= 30
       0      90     153      85     226      84     253      81     418      78
     595      77    1410      77    1469      76 2551.74   73.68 2560.11   66.22
 2608.77   64.92  2628.7   66.79 2657.91   67.21 2663.09   72.19 2693.21   72.81
 2973.99   70.97 3023.96   69.39 3034.21   64.86 3072.54   69.06  3080.4    70.9
 3133.99   71.12 3943.43   72.09 4018.76   70.19 4044.08   71.52    4362      75
    4383      76    4409      79    4439      80    4494      86 4558.25      90
#Mann= 7 ,-1 , 0
       0     .12       0 2551.74     .05       0 2693.21     .12       0
 2973.99     .05       0 3133.99     .12       0 3943.43     .05       0
 4044.08     .12       0
#XS Ineff= 2 , 0
Permanent Ineff=
       F       F
Bank Sta=2551.74,2693.21
XS Rating Curve= 0 ,0
Exp/Cntr=0.5,0.3

Type RM Length L Ch R = 1 ,110     ,45,40,80
BEGIN DESCRIPTION:
Stn 17+10
END DESCRIPTION:
#Sta/Elev= 30
       0      90     235      83     284      80     376      78     581      77
    1405      77    1477      76    2230      75    2333      73    2441      74
 2522.62   72.86  2525.2   67.88 2532.33   65.62 2564.01   65.01 2622.08   67.08
 2629.64   72.08 2635.86   72.26 2936.66   70.91 2983.21   69.01 2994.77   63.98
 3023.12   67.12 3048.67   71.74 3096.66   71.17  3920.3   71.84 3976.28   70.42
 4021.91   71.47    4348      75    4432      82    4467      88 4532.65      90
#Mann= 7 ,-1 , 0
       0     .12       0 2522.62     .05       0 2635.86     .12       0
 2936.66     .05       0 3096.66     .12       0  3920.3     .05       0
 4021.91     .12       0
#XS Ineff= 2 , 0
Permanent Ineff=
       F       F
Bank Sta=2522.62,2635.86
XS Rating Curve= 0 ,0
Exp/Cntr=0.5,0.3

Type RM Length L Ch R = 1 ,100     ,174,168.67,113.33
BEGIN DESCRIPTION:
Stn 17+50
END DESCRIPTION:
#Sta/Elev= 30
       0      90     129      86     241      85     279      81     334      80
     364      78    1380      77    1468      76    2150      75 2525.65   73.36
  2529.2   64.38 2606.63   66.88 2617.88    71.9 2628.16   72.23  2926.4   70.77
 2972.61   69.69  2982.8   65.06 3003.85   62.71 3023.82   64.67 3039.77   68.62
  3047.3   71.52 3082.57   70.63 3934.43   71.12 3964.38    70.2 4024.82    71.2
    4390      74    4417      75    4482      86    4505      89 4528.44      90
#Mann= 7 ,-1 , 0
       0     .12       0 2525.65     .05       0 2628.16     .12       0
  2926.4     .05       0 3082.57     .12       0 3934.43     .05       0
 4024.82     .12       0
#XS Ineff= 2 , 0
Permanent Ineff=
       F       F
Bank Sta=2525.65,2628.16
XS Rating Curve= 0 ,0
Exp/Cntr=0.5,0.3

Type RM Length L Ch R = 1 ,90      ,142.67,173.33,152.67
#Sta/Elev= 30
       0      90     193      81     317      79    1302      78    1560      76
    1600      75    2288      74    2690      73    2812      72    3118      72
    3137      73 3176.35   73.36  3179.9   64.02 3257.33   66.88 3268.58    71.9
 3276.96   72.19  3982.2   71.12 4012.15    70.2 4072.59    71.2    4154      72
    4169      73    4472      74    4500      75    4517      79    4550      83
    4644      86    4979      87    4987      88    5065      89    5080      90
#Mann= 5 ,-1 , 0
       0     .12       0 3176.35     .05       0 3276.96     .12       0
  3982.2     .05       0 4072.59     .12       0
#XS Ineff= 2 , 0
Permanent Ineff=
       F       F
Bank Sta=3176.35,3276.96
XS Rating Curve= 0 ,0
Exp/Cntr=0.5,0.3

Type RM Length L Ch R = 1 ,80      ,123,151.5,98.5
#Sta/Elev= 30
       0      90      84      88     254      82     363      80     374      79
     426      78    1372      77    1381      76    1553      75    2347      74
    2490      73    2596      71    2609      72    2688      73 3145.05   73.36
  3148.6   63.66 3226.03   66.88 3237.28    71.9 3245.66   72.19    3498    71.5
    4002    72.5 4021.66   71.12 4051.61    70.2 4112.05    71.2    4672      74
    4716      77    4735      80    4777      83    4914      85    5089      90
#Mann= 5 ,-1 , 0
       0     .12       0 3145.05     .05       0 3245.66     .12       0
 4021.66     .05       0 4112.05     .12       0
#XS Ineff= 2 , 0
Permanent Ineff=
       F       F
Bank Sta=3145.05,3245.66
XS Rating Curve= 0 ,0
Exp/Cntr=0.5,0.3